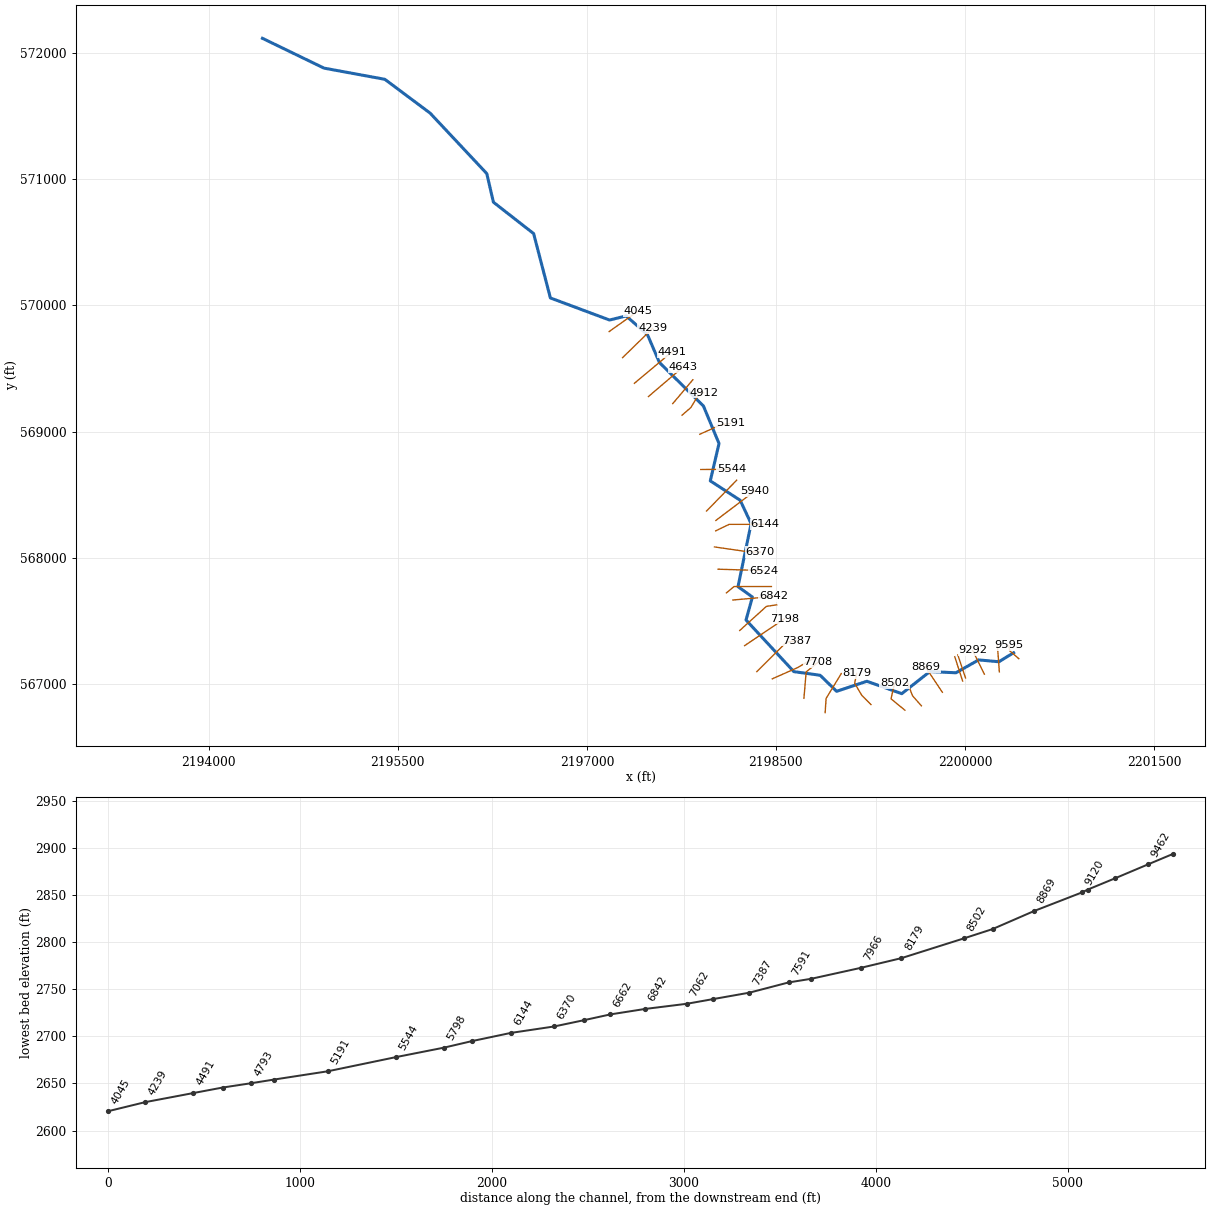
--- BIGRN_1.prj (project) ---

Proj Title=BIGRN_1
Current Plan=p01
Default Exp/Contr=0,0
English Units
Geom File=g01
Flow File=f01
Plan File=p01
BEGIN DESCRIPTION:
----------MODEL BY WOOD PLC 2022----------
AFH study
Randolph County, WV
HEC-RAS Version: RAS 6.2
Vertical Datum: NAVD88
Projection: NAD 1983 StatePlane West Virginia S FIPS 4702 (US Feet)
Terrain: 1-meter LIDAR (FEMA Region III 3DEP collected 2016-2018)
Land Use: 2019 NLCD
Hydrologic Method:
WV SIR2010-5033 regression equations
Additional Model Notes:
None
END DESCRIPTION:
DSS Export Rating Curves= 0
DSS Export Rating Curve Sorted= 0
DSS Export Volume Flow Curves= 0
DXF OffsetX= 0
DXF OffsetY= 0
DXF ScaleX= 0
DXF ScaleY= 0

--- BIGRN_1.p01 (plan) ---

Plan Title=Floodplain
Program Version=6.20
Short Identifier=Floodplain
Geom File=g01
Flow File=f01
Subcritical Flow
K Sum by GR= 0
Std Step Tol= 0.01
Critical Tol= 0.01
Num of Std Step Trials= 20
Max Error Tol= 0.3
Flow Tol Ratio= 0.001
Split Flow NTrial= 30
Split Flow Tol= 0.02
Split Flow Ratio= 0.02
Log Output Level= 0
Friction Slope Method= 1
Unsteady Friction Slope Method= 2
Unsteady Bridges Friction Slope Method= 1
Parabolic Critical Depth
Global Vel Dist= 0 , 0 , 0
Global Log Level= 0
CheckData=True
Encroach Param=-1 ,0,0, 0
Mapping Interval=1HOUR
Computation Time Step Use Courant=        0
Computation Time Step Use Time Series=    0
Computation Time Step Count To Double=0
Computation Time Step Max Doubling=0
Computation Time Step Max Halving=0
Computation Time Step Residence Courant=0
Run HTab= 0
Run UNet= 0
Run Sediment= 0
Run PostProcess= 0
Run WQNet= 0
Run RASMapper=-1
UNET Theta= 0
UNET Theta Warmup= 0
UNET ZTol= 0
UNET ZSATol= 0
UNET MxIter= 0
UNET Max Iter WO Improvement= 0
UNET MaxInSteps= 0
UNET DtIC= 0
UNET DtMin= 0
UNET MaxCRTS= 0
UNET WFStab= 0
UNET SFStab= 0
UNET WFX= 1
UNET SFX= 1
UNET Gravity=32.174
UNET 1D Methodology=Finite Difference
UNET DSS MLevel= 1
UNET Pardiso=0
UNET DZMax Abort= 0
UNET Use Existing IB Tables= 0
UNET Froude Reduction=False
UNET Froude Limit= 0
UNET Froude Power= 0
UNET D1 Cores= 0
UNET WindReference=Eulerian
UNET WindDragFormulation=Hsu (1988)
UNET D2 Coriolis=0
UNET D2 Cores= 0
UNET D2 Theta= 1
UNET D2 Theta Warmup= 1
UNET D2 Z Tol= 0.01
UNET D2 Volume Tol= 0.01
UNET D2 Max Iterations= 20
UNET D2 Equation= 0
UNET D2 RampUpFraction=0.1
UNET D2 TimeSlices= 1
UNET D2 Turbulence Formulation=Non-Conservative (original)
UNET D2 Eddy Viscosity=0.3
UNET D2 Transverse Eddy Viscosity=0.1
UNET D2 Smagorinsky Mixing=0
UNET D2 BCVolumeCheck=0
UNET D2 Cores=0
UNET D2 SolverType=PARDISO (Direct)
UNET D2 Minimum Iterations= 2147483647
UNET D2 Maximum Iterations= 2147483647
UNET D2 Restart Number= 10
UNET D2 Relaxation Coeff=1.3
UNET D2 SOR Precondition Iterations= 10
UNET D2 ILUT Maximum Fill= 8
UNET D2 ILUT Tolerance=1E-08
UNET D1D2 MaxIter= 0
UNET D1D2 ZTol=0.01
UNET D1D2 QTol=0.1
UNET D1D2 MinQTol=1
Write IC File= 0
Write IC File at Fixed DateTime=0
Write IC File at Sim End=0
Echo Input=False
Echo Parameters=False
Echo Output=False
Write Detailed= 0
HDF Write Warmup=0
HDF Write Time Slices=0
HDF Flush=0
HDF Compression= 1
HDF Chunk Size= 1
HDF Spatial Parts= 1
HDF Use Max Rows=0
HDF Fixed Rows= 1
Calibration Method= 0
Calibration Iterations= 20
Calibration Max Change=0.05
Calibration Tolerance=0.2
Calibration Maximum=1.5
Calibration Minimum=0.5
Calibration Optimization Method= 1
WQ AD Non Conservative
WQ ULTIMATE=-1
WQ Max Comp Step=1HOUR
WQ Output Interval=15MIN
WQ Output Selected Increments= 0
WQ Output face flow=0
WQ Output face velocity=0
WQ Output face area=0
WQ Output face dispersion=0
WQ Output cell volume=0
WQ Output cell surface area=0
WQ Output cell continuity=0
WQ Output cumulative cell continuity=0
WQ Output face conc=0
WQ Output face dconc_dx=0
WQ Output face courant=0
WQ Output face peclet=0
WQ Output face adv mass=0
WQ Output face disp mass=0
WQ Output cell mass=0
WQ Output cell source sink temp=0
WQ Output nsm pathways=0
WQ Output nsm derived pathways=0
WQ Create Restart=0
WQ Fixed Restart=0
WQ System Summary=0
WQ Write To DSS=0
Sorting and Armoring Iterations= 10
XS Update Threshold= 0.02
Bed Roughness Predictor= 0
Hydraulics Update Threshold= 0.02
Energy Slope Method= 1
Volume Change Method= 1
Sediment Retention Method= 0
Sediment TS Multiplier= 1
Warm Up Method= 0
XS Weighting Method= 0
Number of US Weighted Cross Sections= 1
Number of DS Weighted Cross Sections= 1
Upstream XS Weight=0
Main XS Weight=1
Downstream XS Weight=0
Number of DS XS's Weighted with US Boundary= 1
Upstream Boundary Weight= 1
Weight of XSs Associated with US Boundary= 0
Number of US XS's Weighted with DS Boundary= 1
Downstream Boundary Weight= 0.5
Weight of XSs Associated with DS Boundary= 0.5
Percentile Method= 0
Sediment Output Level= 3
Mass or Volume Output= 0
Output Increment Type= 1
Profile and TS Output Increment= 1
Transport Output Increment 1
XS Output Flag= 0
XS Output Increment= 10
Read HDF5 Sediment Hotstart= 0
Sediment Hotstart Type= 0
Write Gradation File= 0
Read Gradation Hotstart= 0
Write HDF5 File= 1
Write Binary Output= 1
Write DSS Sediment File= 0
DSS Sediment Output Type= 1
SV Curve= 0
Specific Gage Flag= 0
Subcell Erosion Methods= 0
Subcell Deposition Methods= 0
Advection Scheme= 1
Matrix Solver= 0
Implicit Weighting Factor= 1
Maximum Outer Loop Convergence Iterations= 5
Convergence Maximum Absolute= 0.001
Convergence RMSE= 0.0001
Grain Fractions Max Abs Error= 0.001
Max Subgrid Regions= 1
Max Subgrid Length Scale= 3.402823E+38
Initial Layer Thickness= 3.402823E+38
Min Layer Thickness= 3.402823E+38
Max Layer Thickness= 3.402823E+38
Number of Layers= 5

--- BIGRN_1.f01 (steady flow) ---

Flow Title=Flow
Program Version=6.20
Number of Profiles= 1
Profile Names=P100yr
River Rch & RM=BIGRN_1,Main,9595
     420
River Rch & RM=BIGRN_1,Main,7387
     560
River Rch & RM=BIGRN_1,Main,4912
     636
River Rch & RM=BIGRN_1,Main,2793
     746
Boundary for River Rch & Prof#=BIGRN_1,Main            , 1
Up Type= 0
Dn Type= 3
Dn Slope=0.04421
DSS Import GetInterval= 0
DSS Import GetPeak= 0
DSS Import FillOption= 0

--- BIGRN_1.g01 (geometry) ---

Geom Title=Geometry
Program Version=6.20

River Reach=BIGRN_1         ,Main
Reach XY= 30
     2200386.359      567245.846     2200269.475      567174.345
     2200108.582      567188.988     2199928.894      567086.991
     2199721.658      567096.549     2199498.773      566921.193
     2199221.971      567019.717     2198981.845      566939.856
2198850.88553889567067.304614811     2198642.394      567095.975
     2198262.837      567505.406     2198313.747      567687.461
      2198199.34      567769.806     2198303.246      568269.596
     2198216.326      568454.798     2197979.288      568608.609
     2198048.675      568904.554     2197924.842      569202.316
     2197575.642      569546.977     2197481.024      569767.463
     2197311.508      569916.318     2197179.983      569883.869
2196710.49589814570058.948183351      2196577.48      570569.193
2196258.33530797570818.169674605     2196205.503      571045.327
2195755.51310362571524.951468563     2195396.581      571792.649
     2194913.836      571881.265     2194425.295      572117.723

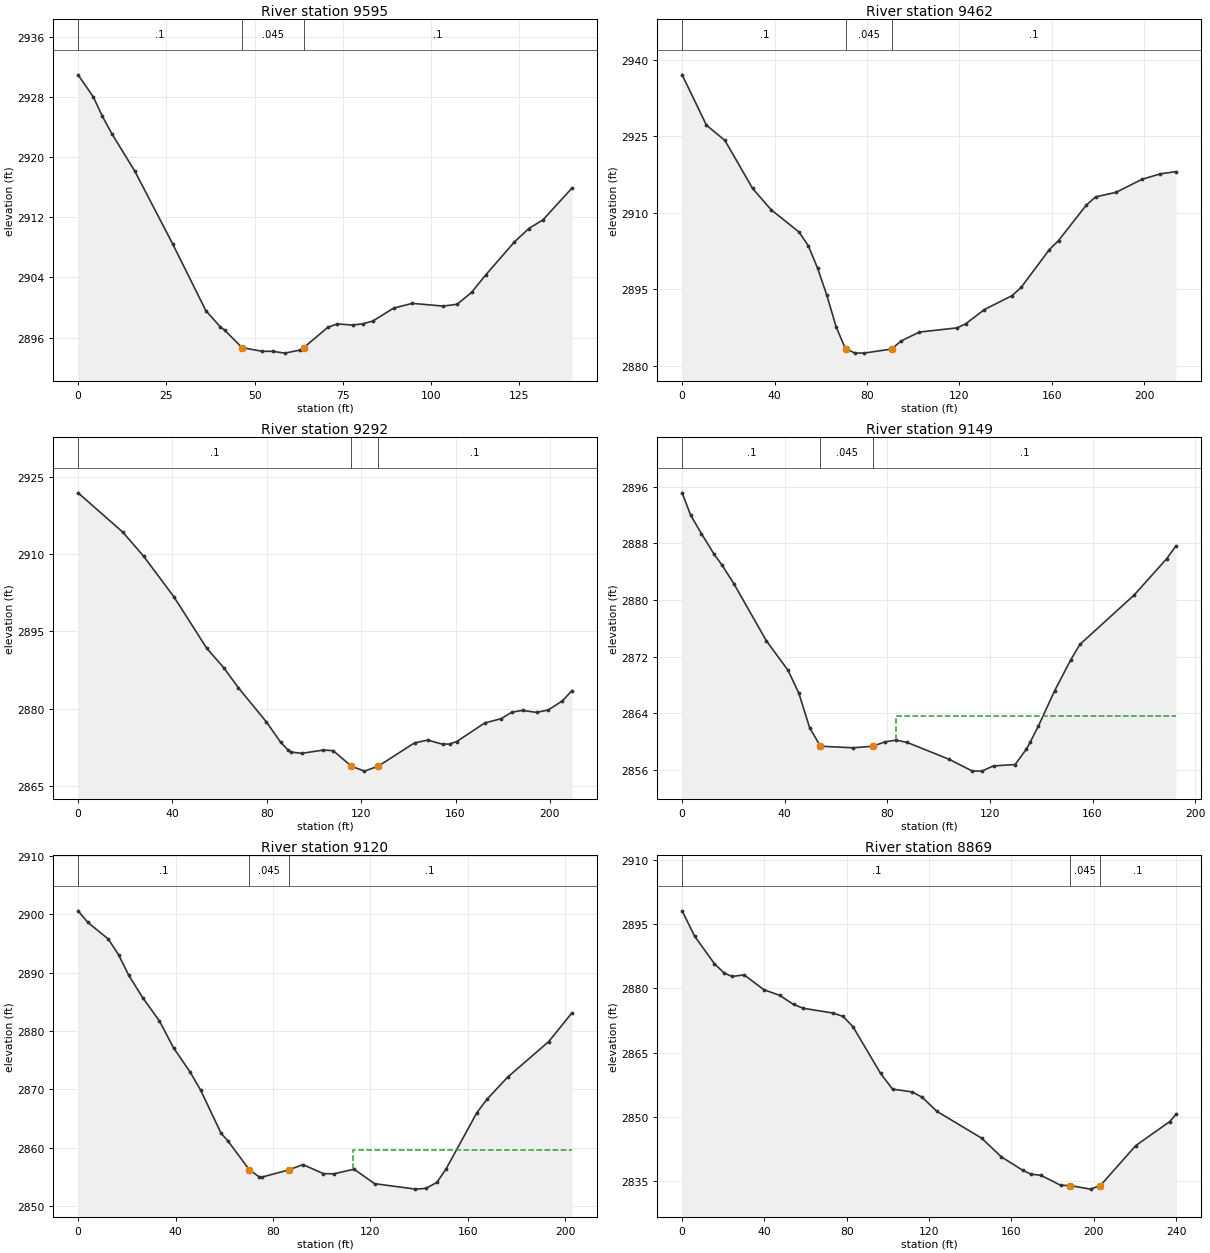
Type RM Length L Ch R = 1 ,9595    ,141.7,133.7,127.5
XS GIS Cut Line= 3
2200427.39234087567198.5922132832200355.28342692567261.769020386
2200348.24362047567305.205832185
#Sta/Elev= 30
       0 2930.91     4.3 2927.98     6.9 2925.38     9.6 2923.06    16.1 2918.09
    26.8 2908.44    36.2 2899.58    40.3 2897.42    41.5 2897.01   46.442894.676
    52.1 2894.19    55.1 2894.18    58.6 2893.94    62.8 2894.34   63.942894.676
    70.7 2897.35    73.4 2897.82    77.8 2897.67    80.6 2897.83    83.5  2898.2
    89.4 2899.92    94.7 2900.55   103.4 2900.19   107.4 2900.43   111.5 2902.02
   115.5 2904.33   123.6  2908.7   127.7 2910.49   131.7 2911.64   139.9 2915.85
#Mann= 3 ,-1,0
       0      .1       0   46.44    .045       0   63.94      .1       0
Bank Sta=46.44,63.94
XS Rating Curve= 0 ,0
Exp/Cntr=0.3,0.1

Type RM Length L Ch R = 1 ,9462    ,168.7,170.1,171.4
XS GIS Cut Line= 2
 2200273.1624354567094.7442093092200257.44711093567307.844009198
#Sta/Elev= 30
       0 2937.05    10.5 2927.18    18.5  2924.2    30.5 2914.78    38.5 2910.61
    50.6 2906.23    54.6 2903.55    58.6 2899.17    62.6 2893.88    66.6 2887.72
    70.6 2883.43   71.12 2883.33    74.6 2882.55    78.6 2882.51    90.7 2883.32
    94.7 2884.88   102.7 2886.64     119 2887.46   122.8 2888.28   130.8 2891.05
   142.8 2893.78   146.8 2895.44   158.9 2902.79   162.9 2904.58   174.9 2911.51
   178.9 2913.12   187.8 2914.03     199 2916.57     207 2917.65   213.7 2918.08
#Mann= 3 ,-1,0
       0      .1       0   71.12    .045       0    90.7      .1       0
Bank Sta=71.12,90.7
XS Rating Curve= 0 ,0
Exp/Cntr(USF)=0,0
Exp/Cntr=0.3,0.1

Type RM Length L Ch R = 1 ,9292    ,143.4,142.9,139.1
XS GIS Cut Line= 2
2200154.16250363567076.2607528542200061.56486213567263.970487764
#Sta/Elev= 30
       0 2921.93    18.9 2914.31    27.8  2909.6    40.7 2901.67    54.5 2891.75
    61.9 2887.86    67.9 2884.08    79.8 2877.43    85.8 2873.51    88.8 2872.05
    90.2 2871.57    94.8 2871.32   103.9 2871.95   108.1 2871.84  115.88 2868.81
   121.4 2867.86  127.21 2868.82   142.6 2873.35   148.2 2873.89   154.5 2873.08
   157.5 2873.14   160.5 2873.61   172.4 2877.22   179.4 2878.06   183.9 2879.33
   188.4 2879.65   194.4 2879.27   199.3 2879.75   205.3 2881.51   209.3 2883.48
#Mann= 3 ,-1,0
       0      .1       0  115.88    .045       0  127.21      .1       0
Bank Sta=115.88,127.21
XS Rating Curve= 0 ,0
Exp/Cntr(USF)=0,0
Exp/Cntr=0.3,0.1

Type RM Length L Ch R = 1 ,9149    ,29,29.3,29.2
XS GIS Cut Line= 2
2200004.74469336567046.0267034342199943.76923439567228.638773841
#Sta/Elev= 30
       0 2895.15     3.3 2891.99     7.5 2889.39    12.4  2886.5    15.6 2884.91
    20.2 2882.28    32.8 2874.26    41.3 2870.05    45.5 2866.82    49.7 2861.95
    53.9 2859.34    66.6 2859.12    74.3 2859.34    79.2 2859.97    83.4  2860.2
    87.7 2859.88   104.1 2857.49     113 2855.85   116.8 2855.82   121.4 2856.56
   129.8 2856.75   134.1 2858.88   135.7 2859.92   138.9  2862.2   145.2 2867.17
   151.5 2871.55   155.1 2873.74   176.2  2880.7   188.9 2885.84   192.5 2887.65
#Mann= 3 ,-1,0
       0      .1       0    53.9    .045       0    74.3      .1       0
#XS Ineff= 2 , 0
                           83.44         2863.57
Permanent Ineff=
       F       F
Bank Sta=53.9,74.3
XS Rating Curve= 0 ,0
Exp/Cntr(USF)=0,0
Exp/Cntr=0.3,0.1

Type RM Length L Ch R = 1 ,9120    ,249.7,249.9,252.9
XS GIS Cut Line= 2
2199981.75276052567021.3591495292199919.46372401567214.297135982
#Sta/Elev= 30
       0 2900.62       4 2898.63    12.4 2895.78    16.6 2893.09    20.8 2889.56
    26.5 2885.73    33.4 2881.72    39.2  2877.1      46 2872.96    50.3 2869.86
    58.7 2862.46    61.5 2861.15    70.32856.207    74.2 2855.02    75.5 2854.95
    86.42856.165    92.3 2857.09   100.7 2855.54   104.9  2855.5   113.3  2856.3
   121.7 2853.82   138.5 2852.88   142.7    2853   147.3 2854.03   151.1 2856.37
   163.7 2865.99   167.9 2868.31   176.3 2872.08   193.2 2878.19   202.7  2883.1
#Mann= 3 ,-1,0
       0      .1       0    70.3    .045       0    86.4      .1       0
#XS Ineff= 2 , 0
                          112.92         2859.65
Permanent Ineff=
       F       F
Bank Sta=70.3,86.4
XS Rating Curve= 0 ,0
Exp/Cntr(USF)=0,0
Exp/Cntr=0.3,0.1

Type RM Length L Ch R = 1 ,8869    ,217.9,216.4,215.5
XS GIS Cut Line= 2
 2199820.8707988566932.1597827122199687.75729634567131.687503972
#Sta/Elev= 30
       0 2898.16       6 2892.27    15.7 2885.78    20.5 2883.57    24.3 2882.81
    30.1 2883.19    39.7 2879.71    47.4 2878.39    54.1 2876.27    58.9 2875.37
    73.4 2874.25    78.2 2873.45      83 2871.06    96.4 2860.14   102.2 2856.47
   111.8 2855.81   116.6 2854.57   123.8 2851.26   145.5    2845   155.1 2840.62
   165.6 2837.45   169.5 2836.59   174.3 2836.31   183.9 2833.98   188.6 2833.91
   198.4 2833.08   203.2 2833.92   220.4 2843.27   236.8 2848.84   239.9 2850.54
#Mann= 3 ,-1,0
       0      .1       0   188.6    .045       0   203.2      .1       0
Bank Sta=188.6,203.2
XS Rating Curve= 0 ,0
Exp/Cntr=0.3,0.1

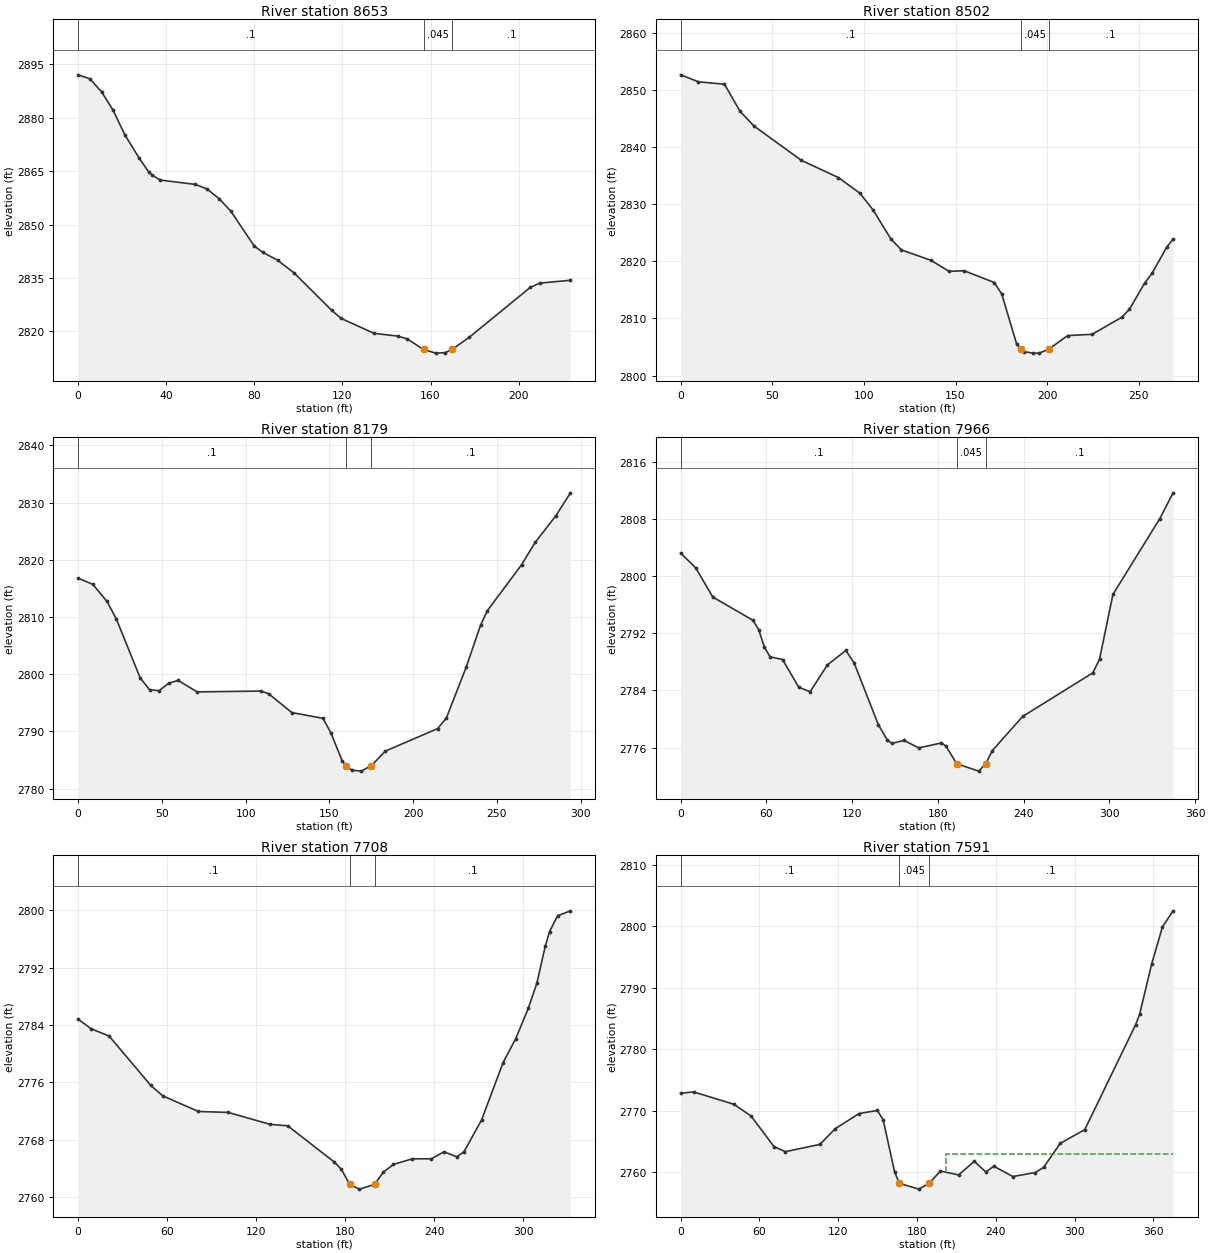
Type RM Length L Ch R = 1 ,8653    ,155.1,150.8,146.7
XS GIS Cut Line= 3
2199654.43025586566825.1632476722199584.30648573566904.809033679
 2199541.7403392567014.163463724
#Sta/Elev= 30
       0 2892.05     5.4 2890.93    10.7 2887.26    15.8 2882.23    21.3 2875.15
    27.6 2868.81      32 2864.84    33.7 2863.87    37.3  2862.5    53.3 2861.28
    58.6 2859.97      64 2857.28    69.3  2853.8      80 2843.96    83.8 2842.23
    90.6 2839.97      98 2836.45   115.1 2825.94   119.4 2823.65   134.3 2819.47
   145.1 2818.68   149.4  2817.9  156.832814.922   162.3  2813.9   166.6 2814.03
   169.8 2814.94   177.6 2818.37   205.2 2832.33   209.5 2833.56   223.5 2834.36
#Mann= 3 ,-1,0
       0      .1       0  156.83    .045       0   169.8      .1       0
Bank Sta=156.83,169.8
XS Rating Curve= 0 ,0
Exp/Cntr(USF)=0,0
Exp/Cntr=0.3,0.1

Type RM Length L Ch R = 1 ,8502    ,315,323.6,326.9
XS GIS Cut Line= 3
2199523.10983385566790.5182958542199413.71396259 566880.45948638
2199441.75787106567004.383584338
#Sta/Elev= 30
       0  2852.6     9.7 2851.38    23.9 2850.96    32.4 2846.23      40 2843.65
    65.9 2837.64    86.1 2834.63    97.8  2831.9     105 2828.97   114.8 2823.85
   120.5 2821.98   136.5 2820.17   146.5 2818.23   154.7 2818.34   171.1 2816.28
   175.2 2814.28   183.4 2805.44   185.9 2804.65   187.5 2804.18   192.3 2803.93
   195.7 2803.93   200.92804.637   211.2    2807   224.5 2807.22   240.8 2810.22
   244.9 2811.61   253.1 2816.14   257.2 2817.88   265.4 2822.56   268.7 2823.85
#Mann= 3 ,-1,0
       0      .1       0   185.9    .045       0   200.9      .1       0
Bank Sta=185.9,200.9
XS Rating Curve= 0 ,0
Exp/Cntr=0.3,0.1

Type RM Length L Ch R = 1 ,8179    ,222.9,212.4,203.6
XS GIS Cut Line= 4
2199254.35201749566834.9184927432199182.22503879566907.324426971
2199125.19716514567003.5300309182199140.93647123567081.798051465
#Sta/Elev= 30
       0 2816.78     8.8 2815.71    17.3 2812.71    22.9 2809.62    37.1 2799.35
    42.7 2797.28    48.4 2797.12    54.1 2798.42    59.7 2798.91    71.1 2796.91
     109 2797.05   113.7 2796.61   127.6 2793.29   146.2 2792.29   150.9 2789.75
   157.6  2784.9  159.772784.021   163.4 2783.24     169 2783.06   175.1 2784.02
   183.4 2786.56   214.6 2790.49   219.8 2792.32   231.6 2801.18   240.2 2808.53
   244.3 2811.11   264.7 2819.13   272.8 2823.02   285.1 2827.67   293.9  2831.7
#Mann= 3 ,-1,0
       0      .1       0  159.77    .045       0   175.1      .1       0
Bank Sta=159.77,175.1
XS Rating Curve= 0 ,0
Exp/Cntr=0.3,0.1

Type RM Length L Ch R = 1 ,7966    ,254,257.8,261.6
XS GIS Cut Line= 3
2198890.77235387566770.7368029362198898.22081113566883.291268251
2199019.05134007567081.089188914
#Sta/Elev= 30
       0 2803.25    10.5  2801.2    22.5 2797.09    50.6 2793.84    54.6 2792.53
    58.6 2790.08    62.6 2788.72    71.3 2788.34    82.6 2784.47    90.6 2783.82
   102.7 2787.59   115.6 2789.61   121.4 2787.86   138.4 2779.18   144.7 2777.04
   147.8 2776.59   156.3 2777.01   166.6 2775.96   182.5 2776.65   185.6 2776.21
  193.232773.733   208.6  2772.7   213.4 2773.72   218.1 2775.58   239.3 2780.36
   288.4 2786.47   293.1 2788.37   302.5 2797.46   335.3 2808.09   344.6  2811.7
#Mann= 3 ,-1,0
       0      .1       0  193.23    .045       0   213.4      .1       0
Bank Sta=193.23,213.4
XS Rating Curve= 0 ,0
Exp/Cntr(USF)=0,0
Exp/Cntr=0.3,0.1

Type RM Length L Ch R = 1 ,7708    ,127.4,117.7,104.4
XS GIS Cut Line= 3
2198722.43521029566884.3555562212198740.02479964567093.229425004
2198834.50056405 567170.73263897
#Sta/Elev= 30
       0 2784.83     8.9 2783.47    20.9 2782.47      49 2775.58      57 2774.13
    81.1 2771.94   101.2 2771.81   129.3 2770.15   141.3 2769.94   172.7 2764.88
   177.4 2763.88   183.1 2761.76   189.5 2761.11  199.82 2761.76   205.5 2763.44
   212.5 2764.56   225.3 2765.34   238.1 2765.34   246.6 2766.32   255.2 2765.62
     260 2766.31   271.9 2770.76   286.4 2778.77   294.9 2782.09   303.5  2786.4
   309.2 2789.87   314.8 2794.99   317.7 2797.02   323.1 2799.24   331.8 2799.93
#Mann= 3 ,-1,0
       0      .1       0   183.1    .045       0  199.82      .1       0
Bank Sta=183.1,199.82
XS Rating Curve= 0 ,0
Exp/Cntr(USF)=0,0
Exp/Cntr=0.3,0.1

Type RM Length L Ch R = 1 ,7591    ,199.7,204,209.2
XS GIS Cut Line= 3
2198471.17592802567038.881264421 2198673.1118805567128.262751582
2198806.35650488567206.057749667
#Sta/Elev= 30
       0 2772.83     9.8 2773.05    40.5 2771.04    53.6 2769.14    71.1 2764.15
    79.8 2763.33   106.1 2764.52   117.7 2767.06   135.9 2769.53   149.8 2770.03
   154.2 2768.56   162.9  2760.1  166.52  2758.2   181.4 2757.24   189.2 2758.18
   197.9 2760.18   211.7 2759.55   223.7 2761.76   232.5 2760.02   238.5 2760.97
     253 2759.29   270.2 2759.94   276.4 2760.77   289.2 2764.69   307.8 2766.91
   346.6 2783.99   349.6 2785.67   358.7 2793.79     367 2799.89   375.1 2802.49
#Mann= 3 ,-1,0
       0      .1       0  166.52    .045       0   189.2      .1       0
#XS Ineff= 2 , 0
                           202.3            2763
Permanent Ineff=
       F       F
Bank Sta=166.52,189.2
XS Rating Curve= 0 ,0
Exp/Cntr(USF)=0,0
Exp/Cntr=0.3,0.1

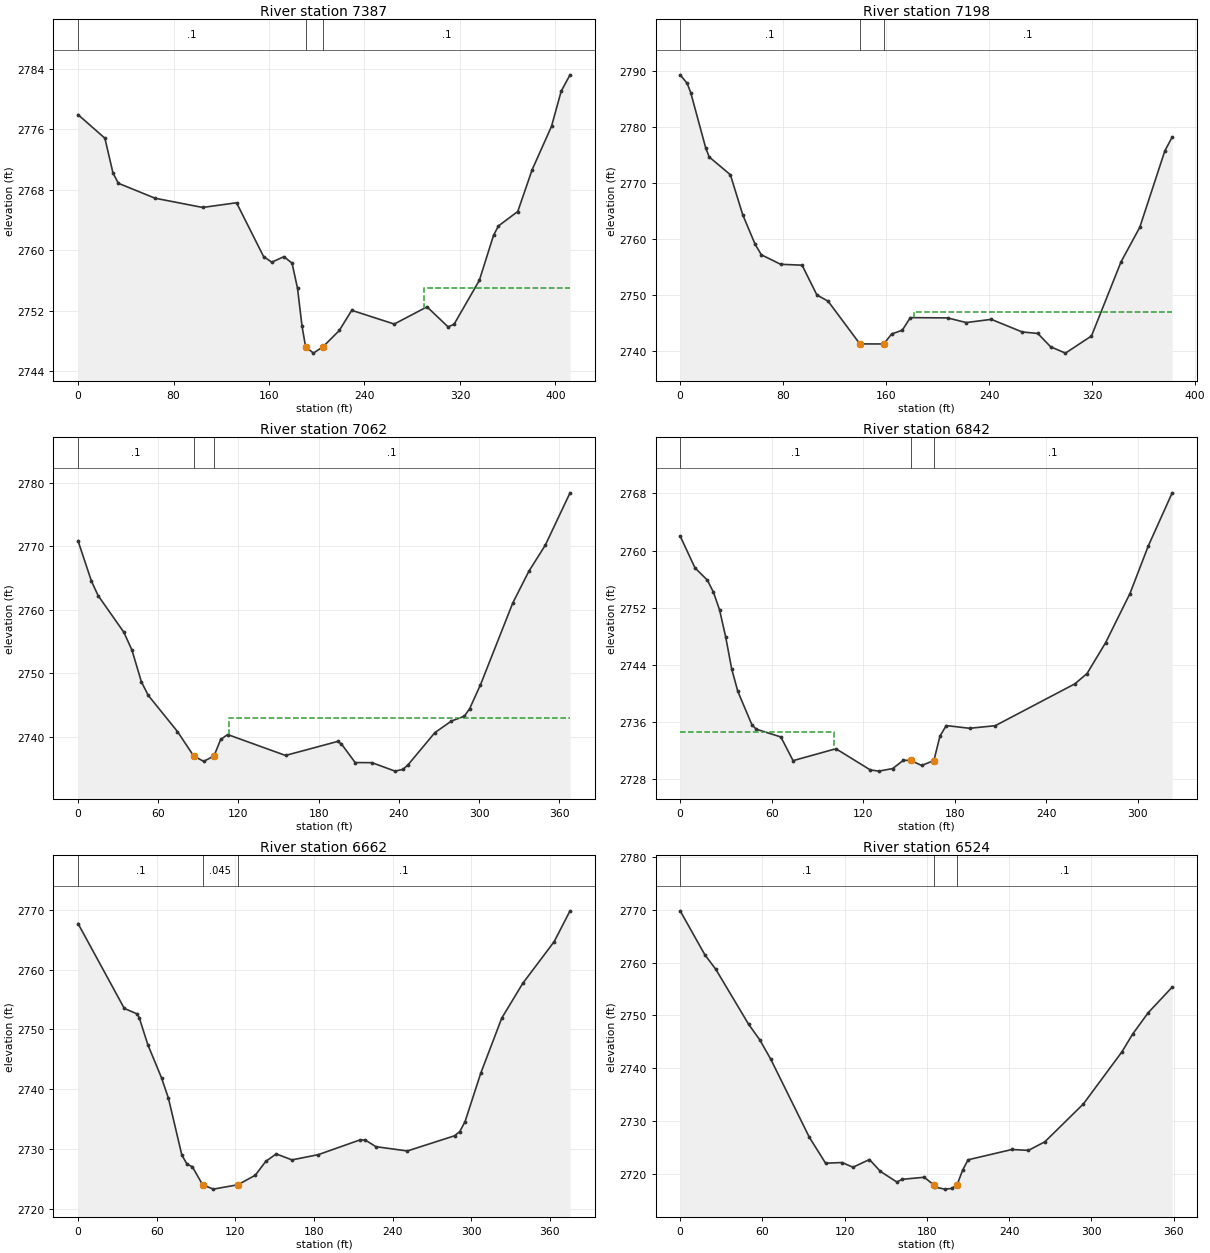
Type RM Length L Ch R = 1 ,7387    ,189.7,188.2,186.7
XS GIS Cut Line= 3
2198348.21833452567095.6295140032198582.80268282567328.532427317
2198663.45794443567341.131226939
#Sta/Elev= 30
       0 2777.96    22.5 2774.84    29.3 2770.23    33.8 2768.87    64.6 2766.89
   104.4 2765.67   132.8 2766.29   155.5 2759.16   162.3 2758.42   172.5 2759.15
   179.3  2758.3   183.9 2754.96   187.7 2749.92  190.642747.244   197.2 2746.38
  205.422747.245   218.9 2749.38   229.3 2752.05   264.9 2750.23   292.4 2752.51
     310 2749.86     315 2750.19   336.2 2756.01   348.1 2761.97   352.2 2763.22
   368.4 2765.13   380.5 2770.68   396.7 2776.42   404.8 2781.07   412.2 2783.23
#Mann= 3 ,-1,0
       0      .1       0  190.64    .045       0  205.42      .1       0
#XS Ineff= 2 , 0
                           289.6            2755
Permanent Ineff=
       F       F
Bank Sta=190.64,205.42
XS Rating Curve= 0 ,0
Exp/Cntr=0.3,0.1

Type RM Length L Ch R = 1 ,7198    ,135.2,136.6,137.9
XS GIS Cut Line= 2
2198251.86024193 567302.060087732198568.93646447567515.473281556
#Sta/Elev= 30
       0 2789.37     5.4 2787.86     8.2 2786.19    19.9 2776.25    22.6 2774.67
      39  2771.5    48.6 2764.34    58.2 2759.07    63.1 2757.17    78.1 2755.48
    94.7 2755.32   106.2    2750   114.9 2748.88  139.62 2741.24   158.1 2741.23
   164.3 2743.02   172.5 2743.68   178.8 2745.94   207.7 2745.89   222.2 2745.06
   241.7 2745.63   265.6 2743.38   277.8 2743.11   287.8 2740.72   299.3 2739.59
   319.5 2742.66   342.5 2755.94     357 2762.08   376.5 2775.77   382.2 2778.24
#Mann= 3 ,-1,0
       0      .1       0  139.62    .045       0   158.1      .1       0
#XS Ineff= 2 , 0
                           181.3            2747
Permanent Ineff=
       F       F
Bank Sta=139.62,158.1
XS Rating Curve= 0 ,0
Exp/Cntr(USF)=0,0
Exp/Cntr=0.3,0.1

Type RM Length L Ch R = 1 ,7062    ,222,219.7,211.7
XS GIS Cut Line= 3
2198213.01094648567422.1691732422198424.64342987567613.478208046
2198506.52111425567625.545973994
#Sta/Elev= 30
       0 2770.89      10 2764.56      15 2762.27    34.3 2756.48    40.3  2753.7
    47.4 2748.69    52.5 2746.56    74.4 2740.85   86.53    2737      94 2736.16
   101.72737.004   106.7  2739.6   111.9 2740.38   155.2 2737.09   194.1 2739.29
   196.9 2738.93   207.3 2735.97   219.9 2735.95   237.1 2734.62   243.1  2734.9
   246.9 2735.63   266.9 2740.68   279.3 2742.51   288.9 2743.26   292.9 2744.45
     301 2748.21   325.2 2761.11   337.2 2766.09   349.5  2770.2     368 2778.44
#Mann= 3 ,-1,0
       0      .1       0   86.53    .045       0   101.7      .1       0
#XS Ineff= 2 , 0
                          112.61         2742.94
Permanent Ineff=
       F       F
Bank Sta=86.53,101.7
XS Rating Curve= 0 ,0
Exp/Cntr=0.3,0.1

Type RM Length L Ch R = 1 ,6842    ,189.5,180.2,175.1
XS GIS Cut Line= 2
2198158.47645069567663.9046687442198479.73153427567692.048437901
#Sta/Elev= 30
       0 2762.03     9.7 2757.57    17.8 2755.85    21.8 2754.16    25.8 2751.69
    29.8 2747.92    33.8 2743.36    37.8 2740.24      47 2735.57    49.9 2734.94
      66 2733.85      74 2730.53   102.1  2732.2   124.6 2729.23   130.2 2729.06
   139.3 2729.42   146.3 2730.58  151.09 2730.56   158.3 2729.85   166.3 2730.55
   170.3 2733.98   174.4 2735.45   189.7 2735.07   206.5 2735.43   258.7  2741.3
   266.7 2742.75   278.8 2747.05   294.8 2753.96   306.9 2760.67   322.5 2768.09
#Mann= 3 ,-1,0
       0      .1       0  151.09    .045       0   166.3      .1       0
#XS Ineff= 2 , 0
          101.05 2734.61
Permanent Ineff=
       F       F
Bank Sta=151.09,166.3
XS Rating Curve= 0 ,0
Exp/Cntr(USF)=0,0
Exp/Cntr=0.3,0.1

Type RM Length L Ch R = 1 ,6662    ,141,138.6,137.4
XS GIS Cut Line= 3
2198107.36735286567720.2178378532198167.62794799567770.842045899
2198464.20667059567770.860022449
#Sta/Elev= 30
       0  2767.7    35.3  2753.5      45 2752.59    46.7 2751.94    53.3 2747.41
    63.7 2741.89      69 2738.46    79.2 2728.97    83.2 2727.44    87.2 2727.03
   95.022724.015   103.2 2723.28     1222724.016   135.2  2725.6   143.2 2727.92
   151.2 2729.17   163.2 2728.17   183.2 2729.04   215.2 2731.52   219.2 2731.48
   227.2 2730.38   251.2 2729.66   287.2  2732.2   291.2 2732.91   295.2 2734.56
   307.2 2742.67   323.2 2751.87   339.2 2757.68   363.2 2764.67   375.3 2769.82
#Mann= 3 ,-1,0
       0      .1       0   95.02    .045       0     122      .1       0
Bank Sta=95.02,122
XS Rating Curve= 0 ,0
Exp/Cntr=0.3,0.1

Type RM Length L Ch R = 1 ,6524    ,154.9,153.5,152.2
XS GIS Cut Line= 2
2198042.15030749567908.1210077842198400.96289645567897.330492242
#Sta/Elev= 30
       0  2769.8      18 2761.48      26 2758.72      50 2748.29    58.1 2745.35
    66.1 2741.69    94.2 2726.93   106.1 2721.99   118.1 2722.12   126.1 2721.23
   138.1 2722.69   146.1 2720.44   158.1 2718.43   162.1 2718.94   178.1 2719.33
  184.85 2717.92   186.1 2717.46     193 2717.08   198.1 2717.21   202.1 2717.92
   206.1 2720.68   210.1 2722.64   242.1 2724.59   254.1 2724.42   266.1 2726.05
   294.2 2733.22   322.2 2743.04   330.2 2746.47   341.5  2750.5     359 2755.35
#Mann= 3 ,-1,0
       0      .1       0  184.85    .045       0   202.1      .1       0
Bank Sta=184.85,202.1
XS Rating Curve= 0 ,0
Exp/Cntr(USF)=0,0
Exp/Cntr=0.3,0.1

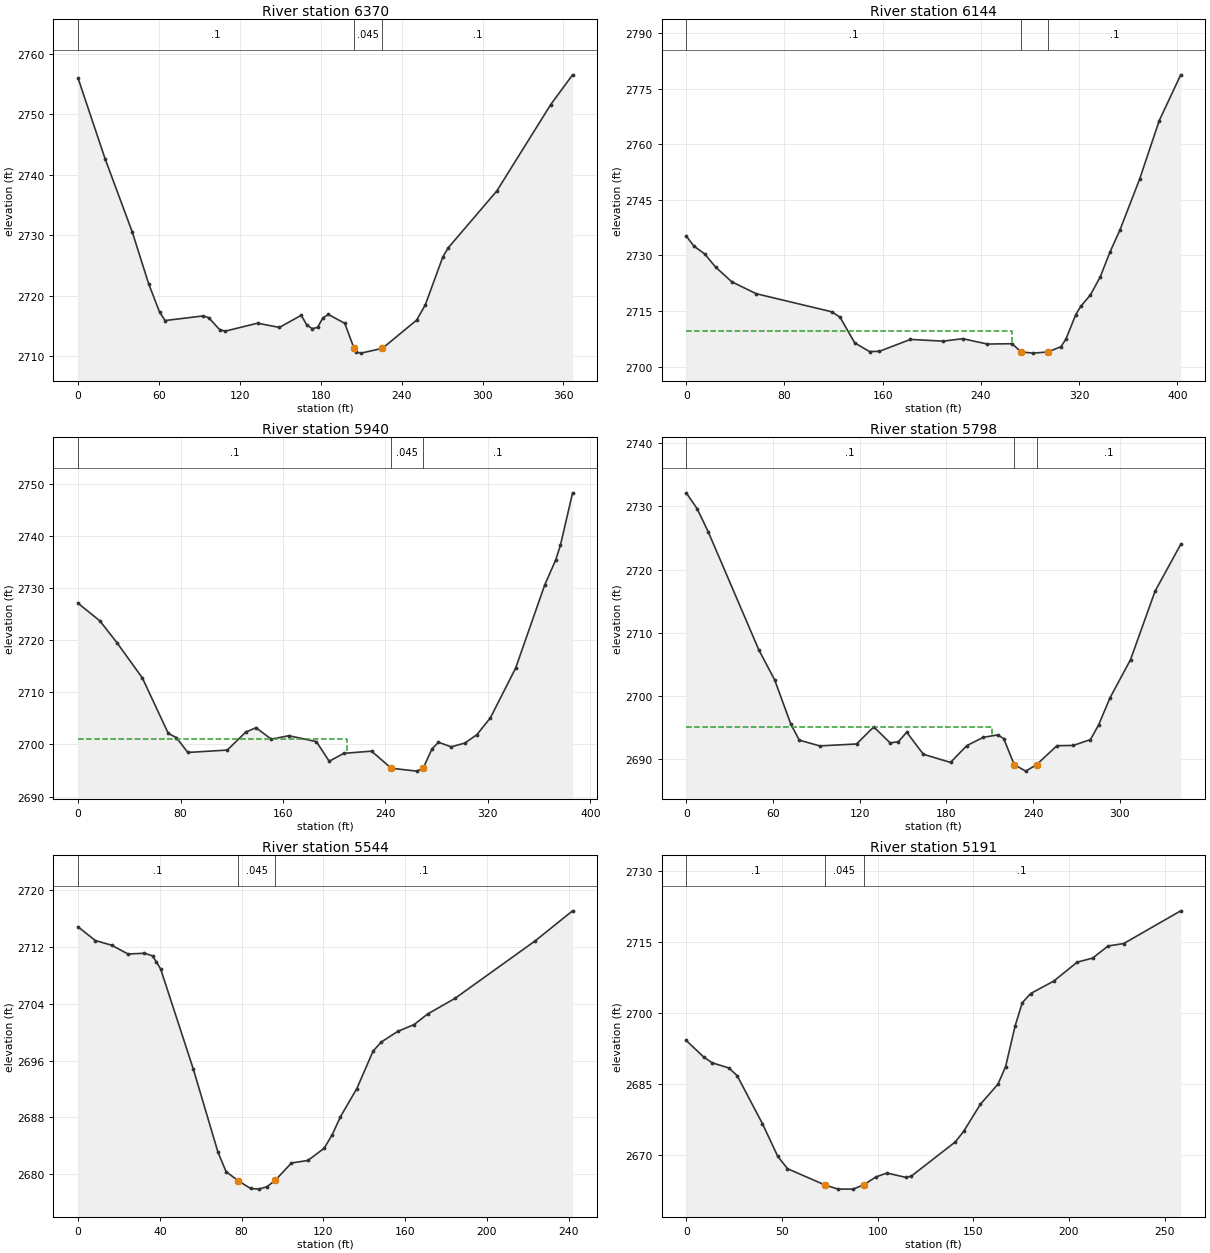
Type RM Length L Ch R = 1 ,6370    ,220.4,226,223.9
XS GIS Cut Line= 3
2198012.37223069568084.7837046322198285.73611644 568045.62202437
2198376.34549431568044.086272203
#Sta/Elev= 30
       0 2755.92      20 2742.63    40.2 2730.49    52.3 2721.97    60.4 2717.28
    64.5 2715.88    92.7 2716.64    96.8 2716.36   104.9 2714.39     109 2714.12
   133.1 2715.44   149.3 2714.74   165.5 2716.75   169.5 2715.19   173.6 2714.54
   177.6 2714.74   181.6 2716.33   185.7 2716.88   197.8 2715.42  204.682711.285
   205.9 2710.71   209.9 2710.49  225.732711.284   251.1 2715.95   257.5 2718.45
   270.5 2726.38   274.6 2727.92   310.6 2737.31   350.6  2751.6   366.8 2756.51
#Mann= 3 ,-1,0
       0      .1       0  204.68    .045       0  225.73      .1       0
Bank Sta=204.68,225.73
XS Rating Curve= 0 ,0
Exp/Cntr(USF)=0,0
Exp/Cntr=0.3,0.1

Type RM Length L Ch R = 1 ,6144    ,193.5,203.6,208.7
XS GIS Cut Line= 3
2198022.62715337568212.4415712722198129.36062407568263.891517357
2198413.66456311568263.738896928
#Sta/Elev= 30
       0 2735.22     6.2 2732.53      15  2730.4    23.9 2726.85    37.2 2722.85
      57 2719.66   118.6 2714.78   125.3 2713.32   137.3 2706.38   149.3 2704.06
   157.3 2704.11   182.6 2707.33   209.3 2706.86   225.3 2707.52   245.3 2706.08
   265.3 2706.17  272.92 2703.95   282.7 2703.63   294.7 2703.95   305.3 2705.38
   309.3  2707.4   317.3 2714.01   321.3 2716.22   329.3 2719.35   337.3 2724.23
   345.3 2730.99   353.3 2736.85   369.3 2750.54   385.3 2766.34   402.8 2778.71
#Mann= 3 ,-1,0
       0      .1       0  272.92    .045       0   294.7      .1       0
#XS Ineff= 2 , 0
          265.23 2709.57
Permanent Ineff=
       F       F
Bank Sta=272.92,294.7
XS Rating Curve= 0 ,0
Exp/Cntr(USF)=0,0
Exp/Cntr=0.3,0.1

Type RM Length L Ch R = 1 ,5940    ,142.3,142.9,147.4
XS GIS Cut Line= 2
  2198023.804765568294.9072722152198331.75146694568527.899901439
#Sta/Elev= 30
       0 2727.14      17 2723.76    30.3 2719.58    50.2 2712.78    70.4 2702.13
    76.7 2701.33    85.7 2698.47   116.5 2698.93   130.9 2702.38   138.9 2703.23
   150.9 2701.02   164.6 2701.69   186.1 2700.55   196.1 2696.78   207.5  2698.3
   229.2 2698.72   244.6 2695.43   264.6 2694.88  269.51 2695.44   276.3 2699.12
   281.4 2700.43   291.4 2699.55   302.1 2700.28   311.4 2701.88     322 2705.13
   341.7 2714.68   364.5 2730.71   373.1 2735.53   376.7 2738.32   386.2 2748.38
#Mann= 3 ,-1,0
       0      .1       0   244.6    .045       0  269.51      .1       0
#XS Ineff= 2 , 0
          210.16 2700.98
Permanent Ineff=
       F       F
Bank Sta=244.6,269.51
XS Rating Curve= 0 ,0
Exp/Cntr=0.3,0.1

Type RM Length L Ch R = 1 ,5798    ,259.5,253.5,246.5
XS GIS Cut Line= 2
2197949.53708513568369.271238164 2198188.6288144568613.823581351
#Sta/Elev= 30
       0 2732.16     7.5 2729.66    15.2 2725.99    50.2 2707.28    61.2  2702.5
    72.4 2695.47    78.2 2692.97    92.3 2692.06   117.8 2692.36   129.7 2695.07
   141.1 2692.52   146.8 2692.74   152.5 2694.23     164 2690.73   182.8 2689.44
   194.1 2692.11   205.5 2693.42   215.5  2693.8   219.6 2693.21  226.852689.091
   234.8 2688.06  242.382689.091   256.4 2692.09   267.7 2692.13   279.6 2693.06
   285.2 2695.37   293.1 2699.67   307.3 2705.73   324.3 2716.59     342 2723.99
#Mann= 3 ,-1,0
       0      .1       0  226.85    .045       0  242.38      .1       0
#XS Ineff= 2 , 0
        211.7849    2695
Permanent Ineff=
       F       F
Bank Sta=226.85,242.38
XS Rating Curve= 0 ,0
Exp/Cntr=0.3,0.1

Type RM Length L Ch R = 1 ,5544    ,345.8,353.1,355
XS GIS Cut Line= 2
2197903.73905886568698.6852388312198145.74090653568700.380527416
#Sta/Elev= 30
       0 2714.86     8.4 2712.94    16.4 2712.28    24.4 2711.04    32.4 2711.14
    36.4 2710.78    38.2 2709.96    40.4 2708.91    56.4 2694.77    68.4 2683.11
    72.4 2680.33    78.22679.069    84.4 2677.95    88.4 2677.86    92.4  2678.2
    96.4 2679.08   104.4 2681.55   112.4  2681.9   120.4 2683.62   124.4 2685.56
   128.4 2688.09   136.4 2692.05   144.4 2697.36   148.4 2698.63   156.4 2700.11
   164.4 2701.08   171.1 2702.58   184.4 2704.77   223.5 2712.85     242 2717.13
#Mann= 3 ,-1,0
       0      .1       0    78.2    .045       0    96.4      .1       0
Bank Sta=78.2,96.4
XS Rating Curve= 0 ,0
Exp/Cntr(USF)=0,0
Exp/Cntr=0.3,0.1

Type RM Length L Ch R = 1 ,5191    ,271.7,279.3,283.6
XS GIS Cut Line= 3
 2197895.8573962568978.2988475222198059.43752778 569051.53093932
2198137.68765326 569063.73512036
#Sta/Elev= 30
       0 2694.22     9.1 2690.74    13.5 2689.52    22.3 2688.42    26.6 2686.81
    39.8 2676.71    47.8 2669.83    52.9 2667.21   72.362663.797    79.2 2662.92
    87.2  2662.9   92.642663.797    99.3  2665.5   104.9 2666.29   114.7 2665.38
   117.5  2665.6   140.6 2672.84     145 2675.08   153.7 2680.77   162.9 2685.01
   166.9 2688.71   171.9 2697.33   175.6 2702.16     180 2704.11   192.1 2706.74
   204.3 2710.71   212.4 2711.58   220.5 2714.13   228.6 2714.63   258.4 2721.53
#Mann= 3 ,-1,0
       0      .1       0   72.36    .045       0   92.64      .1       0
Bank Sta=72.36,92.64
XS Rating Curve= 0 ,0
Exp/Cntr=0.3,0.1

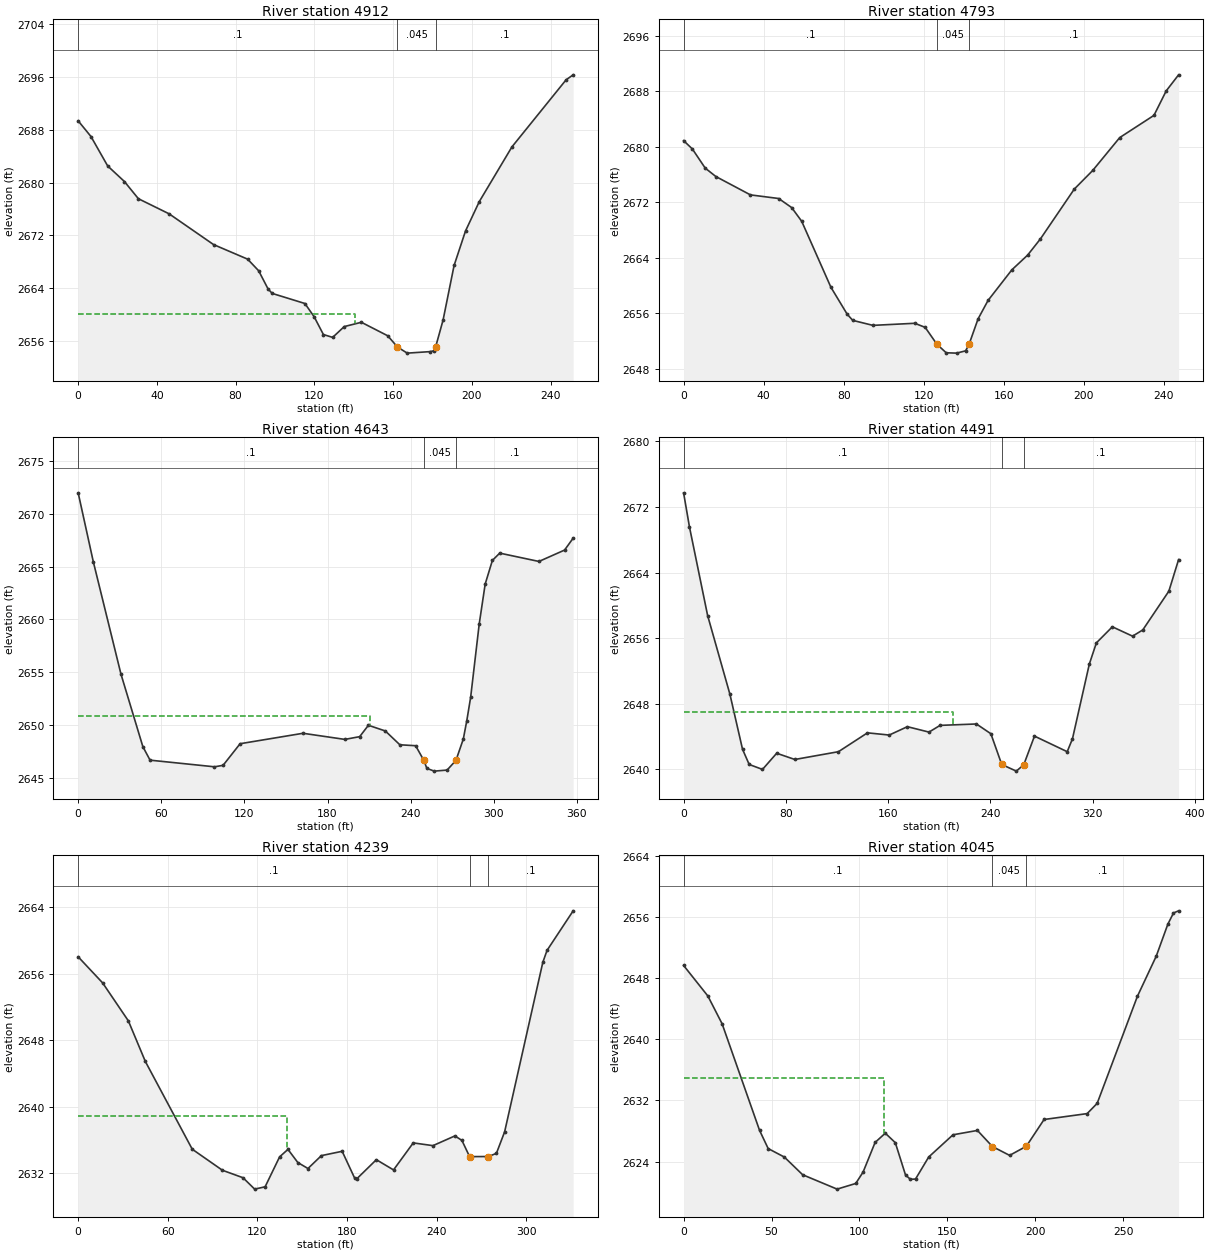
Type RM Length L Ch R = 1 ,4912    ,119.8,118.3,117.2
XS GIS Cut Line= 4
2197755.13374269569129.095178293 2197825.0104663569189.757388896
2197875.69028782569273.4558820052197925.60223325 569308.77818185
#Sta/Elev= 30
       0 2689.38     6.5    2687      15 2682.53    23.5 2680.17    30.6 2677.56
    46.2 2675.27    68.8  2670.6    86.1 2668.39    91.7 2666.63    96.5 2663.86
    98.6 2663.19   115.2 2661.66   119.9 2659.65   124.6 2656.95   129.3 2656.52
   135.2 2658.16   143.9 2658.81   157.3 2656.76  162.222655.057   167.2 2654.13
   178.9 2654.36   180.7 2654.48  181.612655.059   185.4 2659.14     191 2667.43
   196.8 2672.66   203.8 2677.12   220.4 2685.43   247.9  2695.6   251.5 2696.36
#Mann= 3 ,-1,0
       0      .1       0  162.22    .045       0  181.61      .1       0
#XS Ineff= 2 , 0
        140.8058    2660
Permanent Ineff=
       F       F
Bank Sta=162.22,181.61
XS Rating Curve= 0 ,0
Exp/Cntr(USF)=0,0
Exp/Cntr=0.3,0.1

Type RM Length L Ch R = 1 ,4793    ,151.5,150.6,149.9
XS GIS Cut Line= 2
2197681.36724582569220.8952501522197840.75810084569409.916456426
#Sta/Elev= 30
       0 2680.89     4.4 2679.68    10.8 2676.93    16.1 2675.72    33.4 2673.07
    47.5 2672.55      54 2671.24      59 2669.27    73.6 2659.76    81.7 2655.89
    84.5 2654.99    94.6 2654.27   115.5 2654.57   120.7 2653.98  126.572651.542
   131.2 2650.32   136.4 2650.27   140.9  2650.6   142.62651.522   147.1 2655.19
   152.1 2657.86     164 2662.27   171.9  2664.4   178.3 2666.74   195.2 2673.91
   204.4 2676.59   217.9 2681.33     235 2684.53   241.1 2688.05   247.3 2690.37
#Mann= 3 ,-1,0
       0      .1       0  126.57    .045       0   142.6      .1       0
Bank Sta=126.57,142.6
XS Rating Curve= 0 ,0
Exp/Cntr(USF)=0,0
Exp/Cntr=0.3,0.1

Type RM Length L Ch R = 1 ,4643    ,151.6,151.9,152.4
XS GIS Cut Line= 2
2197488.68074169569277.2952624232197760.50887528569509.193839663
#Sta/Elev= 30
       0 2672.01    10.9 2665.49    30.9 2654.81    46.7 2647.93    51.9 2646.65
    98.4 2646.02   104.6 2646.16   116.9 2648.21   162.3  2649.2   192.5 2648.62
   203.2 2648.88   209.5 2649.96   221.7 2649.42   232.2 2648.11   243.6 2648.02
  249.452646.644   251.7 2645.87     257 2645.61   266.3 2645.71   272.7 2646.63
     278 2648.65   280.5 2650.38   283.3 2652.61   289.5 2659.58   293.8 2663.36
     299  2665.6   304.3 2666.29   332.6  2665.5   351.1 2666.58   357.3 2667.71
#Mann= 3 ,-1,0
       0      .1       0  249.45    .045       0   272.7      .1       0
#XS Ineff= 2 , 0
          210.46 2650.86
Permanent Ineff=
       F       F
Bank Sta=249.45,272.7
XS Rating Curve= 0 ,0
Exp/Cntr(USF)=0,0
Exp/Cntr=0.3,0.1

Type RM Length L Ch R = 1 ,4491    ,252.7,251.9,252
XS GIS Cut Line= 2
2197376.84464879569381.9710373282197673.66817778569630.463459259
#Sta/Elev= 30
       0 2673.73     4.6 2669.56    18.8 2658.76    36.2 2649.18    46.1 2642.45
    51.3  2640.6    61.7    2640    72.8 2641.97      87 2641.21   121.1 2642.16
   143.8 2644.46   160.8 2644.19     175 2645.21   191.9 2644.55   200.6 2645.37
     229 2645.54   240.3 2644.35   248.8  2640.6   260.2 2639.79  266.02 2640.57
   274.4 2644.06     300 2642.16   304.1 2643.73   317.3 2652.85   322.8 2655.43
   335.3 2657.39   351.1 2656.25   359.1 2657.01   379.5 2661.74   387.1 2665.59
#Mann= 3 ,-1,0
       0      .1       0   248.8    .045       0  266.02      .1       0
#XS Ineff= 2 , 0
           210.7    2647
Permanent Ineff=
       F       F
Bank Sta=248.8,266.02
XS Rating Curve= 0 ,0
Exp/Cntr(USF)=0,0
Exp/Cntr=0.3,0.1

Type RM Length L Ch R = 1 ,4239    ,196.5,193.8,192.9
XS GIS Cut Line= 2
2197283.58377834569585.7211862282197520.88377481 569817.24387023
#Sta/Elev= 30
       0 2658.01    16.4 2654.87    33.6 2650.31      45 2645.42    76.4 2634.87
    96.6 2632.34   110.4 2631.44   118.2 2630.07   125.2 2630.35   134.9 2633.95
   140.5 2634.85   147.1 2633.27   153.9 2632.55   162.9  2634.1   176.8 2634.62
   185.2 2631.38   186.7 2631.33   199.7 2633.61   211.2 2632.38   224.4 2635.63
   237.6  2635.3   252.3 2636.47     257 2635.93  262.14 2633.98   274.7 2633.99
   280.1 2634.37   285.6 2636.96   311.2 2657.36     314 2658.78   331.5 2663.54
#Mann= 3 ,-1,0
       0      .1       0  262.14    .045       0   274.7      .1       0
#XS Ineff= 2 , 0
          140.09 2638.85
Permanent Ineff=
       F       F
Bank Sta=262.14,274.7
XS Rating Curve= 0 ,0
Exp/Cntr(USF)=0,0
Exp/Cntr=0.3,0.1

Type RM Length L Ch R = 1 ,4045    ,310.8,325.1,329.5
XS GIS Cut Line= 2
2197176.92305176569792.5401145012197406.51800075569955.329844219
#Sta/Elev= 30
       0 2649.64    13.8 2645.65    21.9 2642.02    43.2 2628.09    48.1 2625.71
    57.3  2624.6    67.7 2622.29    87.3 2620.41    97.9 2621.15   102.1 2622.65
   108.9 2626.51   114.7 2627.72   120.4 2626.48   126.2 2622.26     129 2621.69
   131.9 2621.73   139.4 2624.61   153.2 2627.51   167.1 2628.08   175.6 2625.98
   185.4 2624.82  194.912626.011     205 2629.51   229.5 2630.28   235.2 2631.62
   258.1 2645.62   268.8 2650.86   275.4 2655.04   278.6  2656.5   281.5 2656.78
#Mann= 3 ,-1,0
       0      .1       0   175.6    .045       0  194.91      .1       0
#XS Ineff= 2 , 0
          114.13 2634.99
Permanent Ineff=
       F       F
Bank Sta=175.6,194.91
XS Rating Curve= 0 ,0
Exp/Cntr(USF)=0,0
Exp/Cntr=0.3,0.1