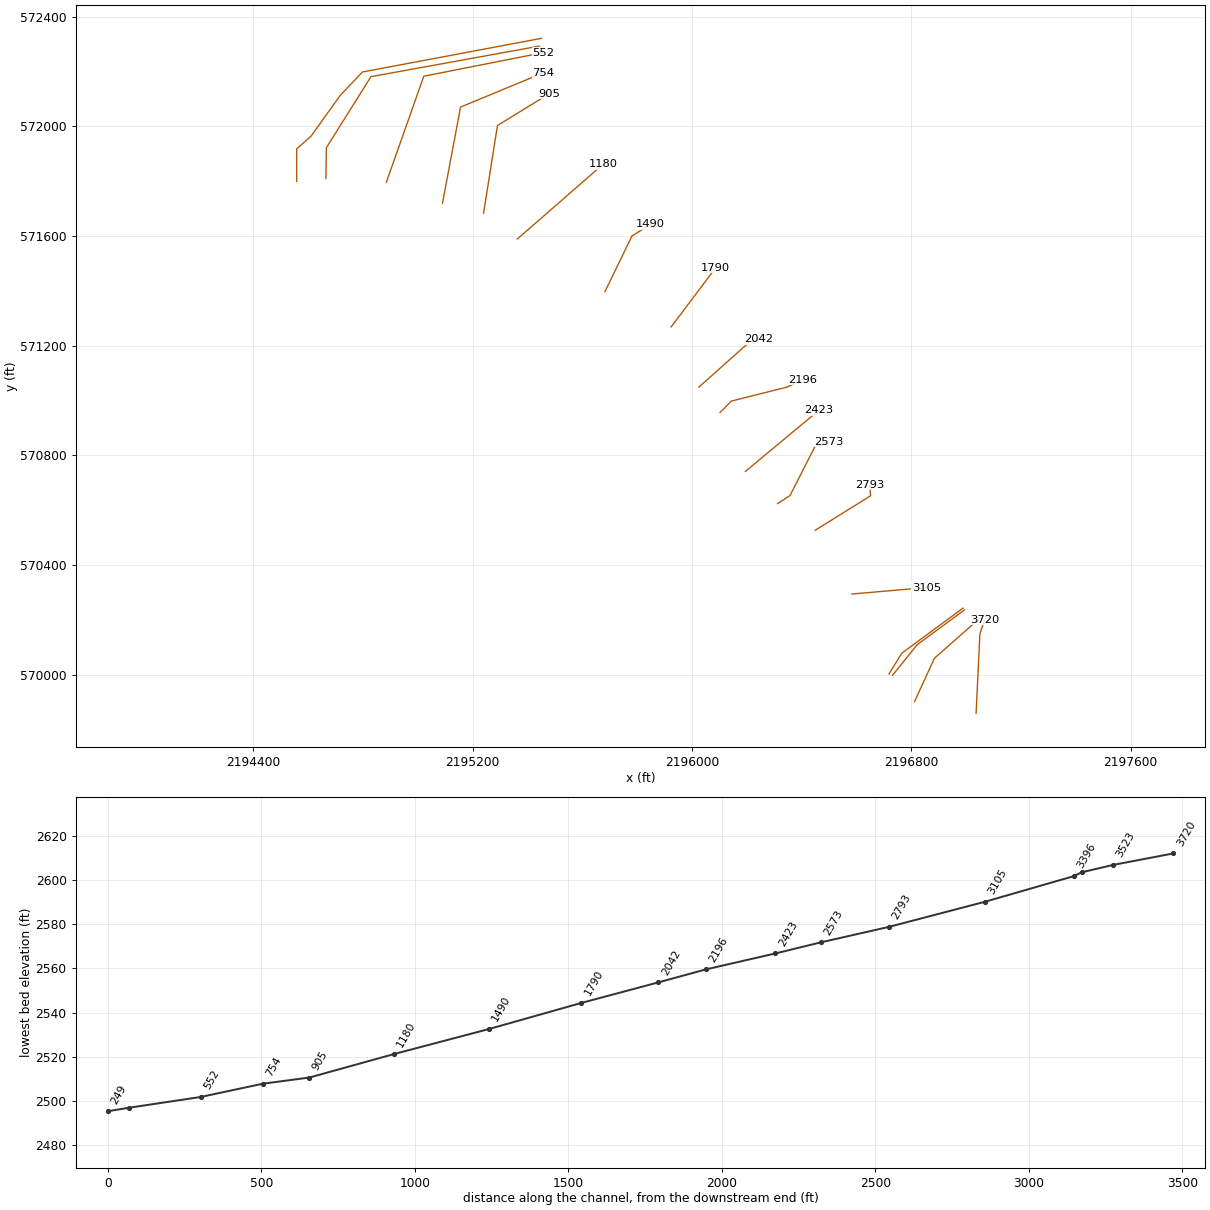
HEC-RAS study BIGRN_1.prj: BIGRN_1

--- BIGRN_1.g01 (geometry) --- (continued)

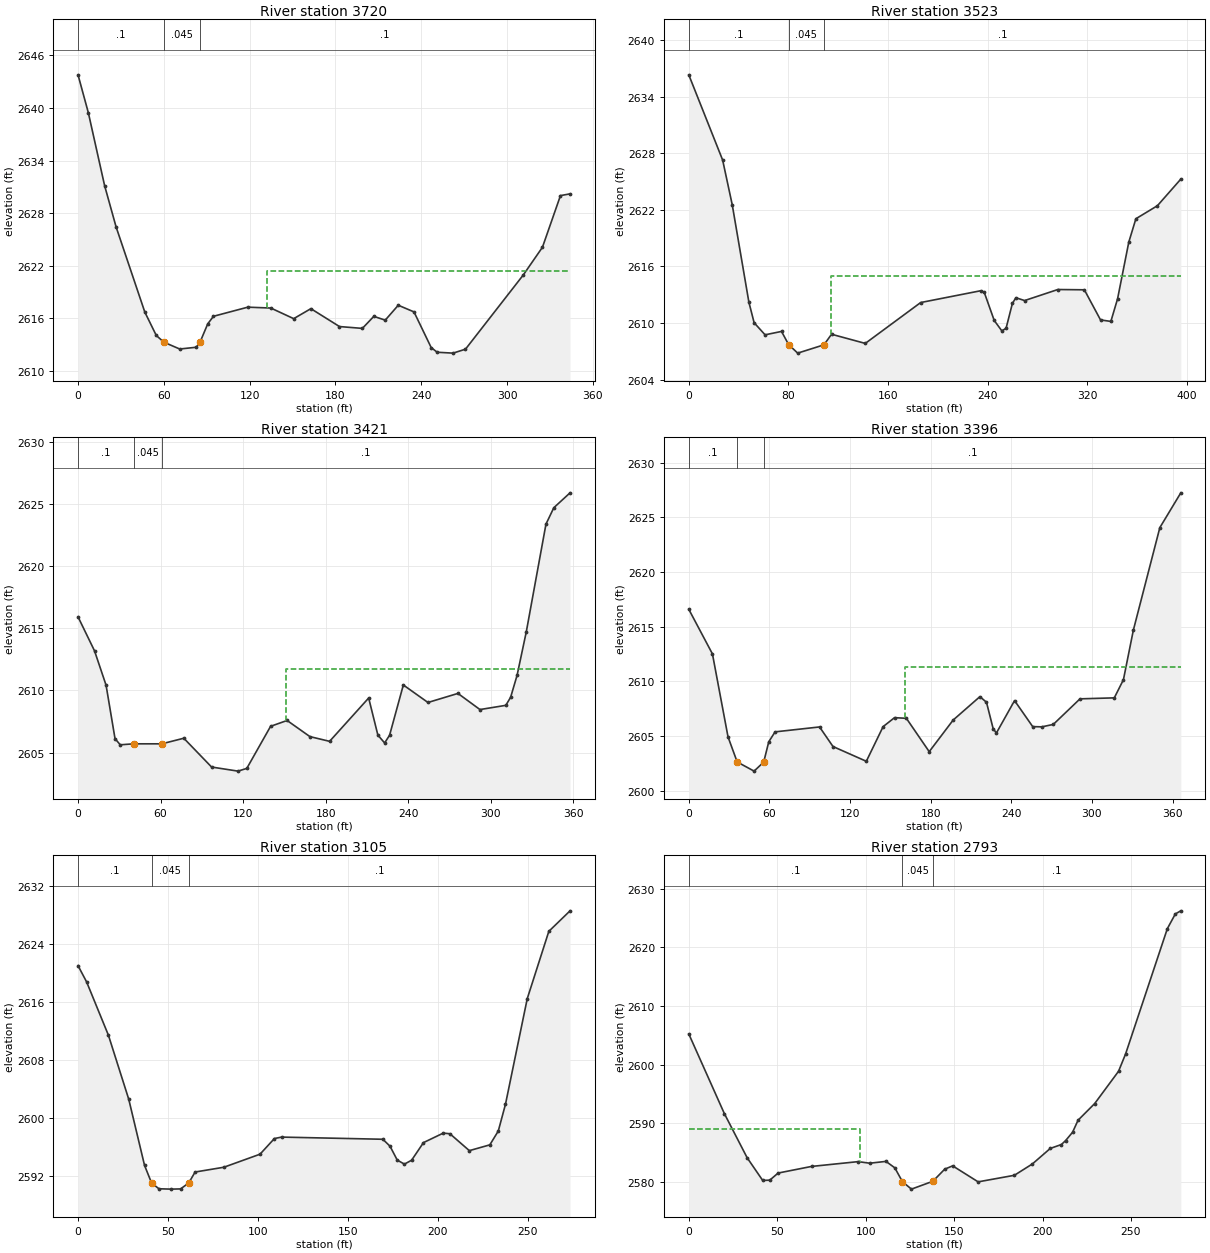
Type RM Length L Ch R = 1 ,3720    ,203.1,197.3,193.1
XS GIS Cut Line= 3
2197036.40172847569858.5774576892197050.22349797570148.066741196
2197067.11677181570199.514438796
#Sta/Elev= 30
       0 2643.78     7.2 2639.47    18.6 2631.14    26.6 2626.45    46.7 2616.73
    54.7 2614.07   59.992613.299    71.1 2612.52    82.7 2612.72    85.32613.296
    90.7 2615.39    94.7 2616.25   118.7 2617.29   134.8 2617.19   150.8 2615.98
   162.8 2617.12   182.8 2615.08   198.8 2614.87   206.8 2616.24   214.8 2615.81
   223.9 2617.51   234.9 2616.75   246.9 2612.69   251.1 2612.15   262.2 2612.05
   270.9  2612.5   311.3 2620.96   324.7 2624.12   337.3 2630.01     344 2630.21
#Mann= 3 ,-1,0
       0      .1       0   59.99    .045       0    85.3      .1       0
#XS Ineff= 2 , 0
                          132.28         2621.43
Permanent Ineff=
       F       F
Bank Sta=59.99,85.3
XS Rating Curve= 0 ,0
Exp/Cntr(USF)=0,0
Exp/Cntr=0.3,0.1

Type RM Length L Ch R = 1 ,3523    ,104.9,101.8,99.3
XS GIS Cut Line= 3
2196811.82141006 569901.478298232196884.41297072570059.740711509
2197050.29829654570206.017210585
#Sta/Elev= 30
       0 2636.31    27.2 2627.28    34.9 2622.55    48.3 2612.21    52.5 2610.04
    61.3 2608.76    74.5 2609.12   80.25 2607.72    87.5 2606.82   108.6  2607.7
   114.7 2608.82   141.8 2607.85   186.3 2612.18   234.5 2613.43   237.3 2613.29
   245.4 2610.28   251.5 2609.18   254.9 2609.45     260 2612.09   262.8 2612.69
   269.8 2612.39   296.5 2613.56   317.8 2613.53   330.8 2610.34   339.1 2610.18
   344.5 2612.58   353.5 2618.58   359.2 2621.06   376.5 2622.44   395.3 2625.26
#Mann= 3 ,-1,0
       0      .1       0   80.25    .045       0   108.6      .1       0
#XS Ineff= 2 , 0
                           114.1            2615
Permanent Ineff=
       F       F
Bank Sta=80.25,108.6
XS Rating Curve= 0 ,0
Exp/Cntr(USF)=0,0
Exp/Cntr=0.3,0.1

Type RM Length L Ch R = 1 ,3421    ,19.6,24.8,22.6
XS GIS Cut Line= 3
2196731.28749111569997.254087038 2196821.0355874 570108.80029717
 2196993.7952743570236.012568322
#Sta/Elev= 30
       0 2615.93      12 2613.19    20.4 2610.42    26.9 2606.12    30.7 2605.62
    40.4  2605.7   60.94  2605.7    76.9 2606.15    97.1 2603.83   116.3  2603.5
   122.7 2603.72     140 2607.11     152 2607.58   168.6 2606.28   182.9  2605.9
   211.3 2609.39     218  2606.4   222.9 2605.77   226.5 2606.39   236.5 2610.44
   254.4 2609.03   276.2 2609.76   292.2 2608.46     311  2608.8   314.5 2609.45
   319.2 2611.22   325.9 2614.73   340.2  2623.4   345.9 2624.72   357.7 2625.92
#Mann= 3 ,-1,0
       0      .1       0    40.4    .045       0   60.94      .1       0
#XS Ineff= 2 , 0
                          151.18          2611.7
Permanent Ineff=
       F       F
Bank Sta=40.4,60.94
XS Rating Curve= 0 ,0
Exp/Cntr(USF)=0,0
Exp/Cntr=0.3,0.1

Type RM Length L Ch R = 1 ,3396    ,297.9,291.1,279
XS GIS Cut Line= 3
2196718.62481026 570002.560940142196765.28226243570078.104525782
2196988.59129338570242.502130811
#Sta/Elev= 30
       0 2616.59    17.6 2612.51    29.2 2604.92      36 2602.63    48.6 2601.79
   55.75 2602.62    59.5 2604.47    64.2 2605.38    97.3 2605.83   107.3 2604.04
   132.1 2602.69   144.6 2605.86   153.1 2606.68   161.9 2606.62   178.9 2603.57
   196.7 2606.46   216.6  2608.6   221.5 2608.09   226.5 2605.66   228.9 2605.28
   242.4 2608.24   255.9 2605.86   262.7 2605.84   271.2 2606.06   291.1  2608.4
   316.6 2608.49   323.4 2610.15   330.8 2614.69   350.5 2624.06   366.1 2627.24
#Mann= 3 ,-1,0
       0      .1       0      36    .045       0   55.75      .1       0
#XS Ineff= 2 , 0
                          160.59         2611.28
Permanent Ineff=
       F       F
Bank Sta=36,55.75
XS Rating Curve= 0 ,0
Exp/Cntr(USF)=0,0
Exp/Cntr=0.3,0.1

Type RM Length L Ch R = 1 ,3105    ,308.1,312.5,316.7
XS GIS Cut Line= 2
2196583.35483916570293.9631970752196855.95084883570317.767355666
#Sta/Elev= 30
       0 2620.98     4.8 2618.72    16.9 2611.38    28.2 2602.55      37 2593.41
   40.922590.979      45 2590.19    51.7 2590.14      57 2590.17   61.542590.978
    65.1  2592.5    81.1 2593.16   101.2 2594.96   109.2 2597.12   113.2 2597.32
   169.5 2597.02   173.5 2596.06   177.5 2594.15   181.5 2593.59   185.5 2594.13
   192.1 2596.56   203.1 2597.87   206.8 2597.78   217.6 2595.45     229 2596.25
   233.7 2598.16   237.7 2601.86   249.8 2616.42   261.8 2625.71   273.6 2628.54
#Mann= 3 ,-1,0
       0      .1       0   40.92    .045       0   61.54      .1       0
Bank Sta=40.92,61.54
XS Rating Curve= 0 ,0
Exp/Cntr(USF)=0,0
Exp/Cntr=0.3,0.1

Type RM Length L Ch R = 1 ,2793    ,213.9,219.7,224.2
XS GIS Cut Line= 3
2196449.28074938570526.5541033922196651.45710569570652.347736586
2196647.94456835570692.270539014
#Sta/Elev= 30
       0 2605.26    20.1 2591.68      33 2584.14    41.8 2580.27    45.8 2580.32
    50.5 2581.53    69.4 2582.66    95.8 2583.48   102.3 2583.21   111.5 2583.52
   116.5 2582.42  120.822580.052   125.9 2578.79     138 2580.13   144.7 2582.19
   149.2 2582.76   163.6 2580.03   184.1 2581.15   194.3 2583.09   204.4 2585.73
   210.7  2586.4   213.1 2587.08     217 2588.49   220.1 2590.54   229.5 2593.38
     243 2598.89     247 2601.86   270.6 2623.22   275.1 2625.72   278.2 2626.25
#Mann= 3 ,-1,0
       0      .1       0  120.82    .045       0     138      .1       0
#XS Ineff= 2 , 0
           96.65 2588.98
Permanent Ineff=
       F       F
Bank Sta=120.82,138
XS Rating Curve= 0 ,0
Exp/Cntr(USF)=0,0
Exp/Cntr=0.3,0.1

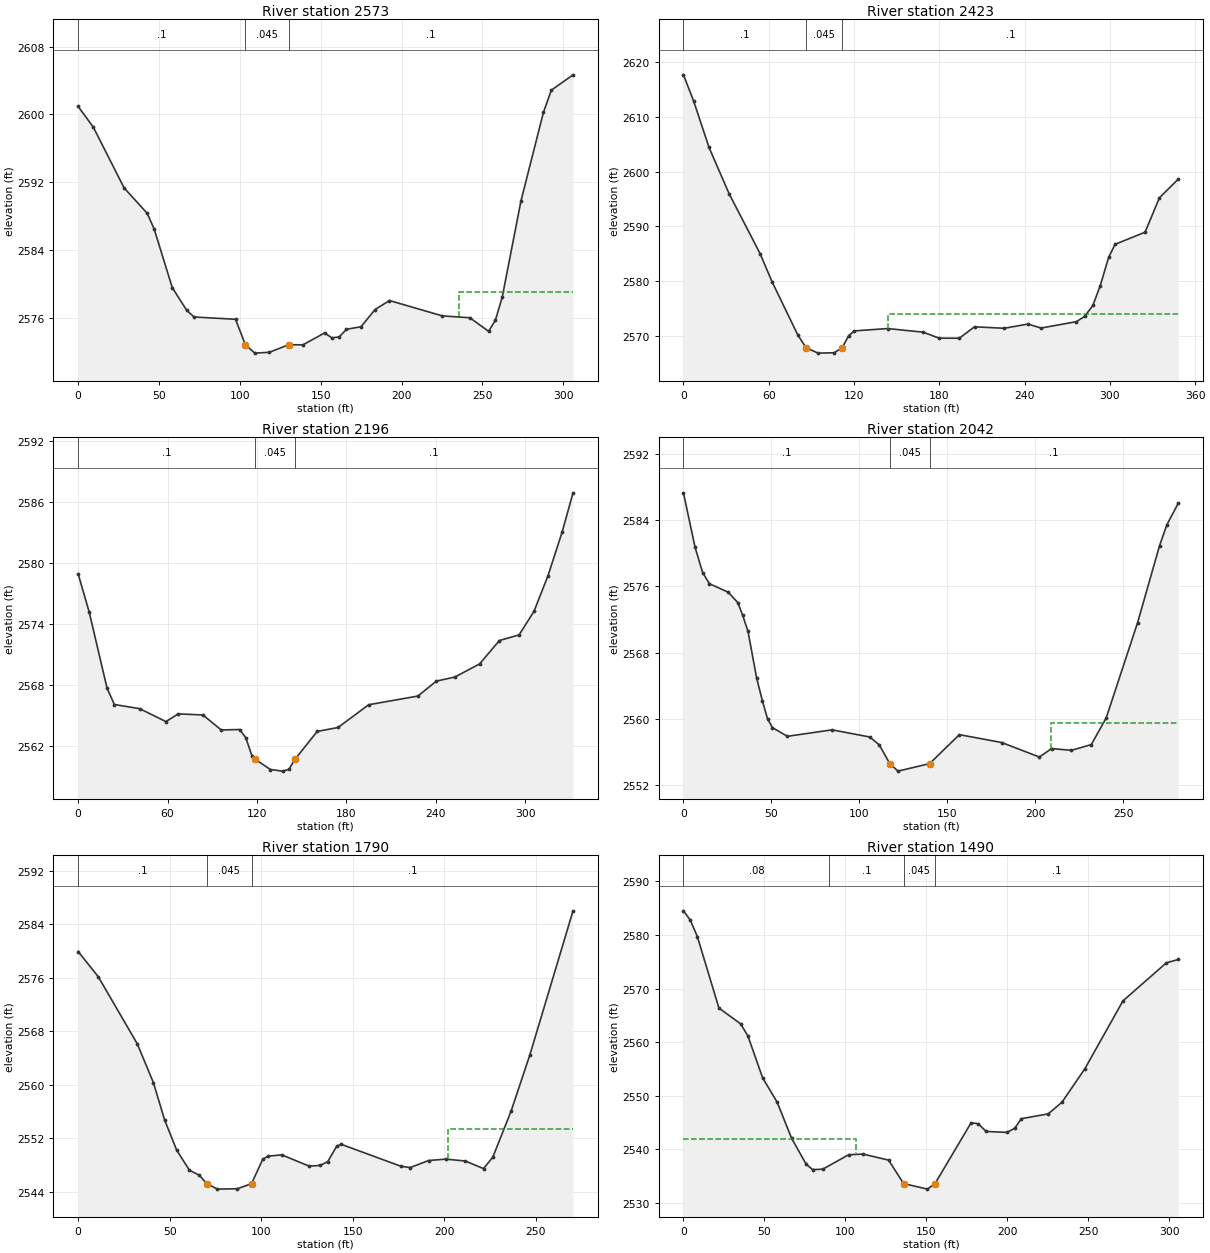
Type RM Length L Ch R = 1 ,2573    ,155.1,149.5,144.5
XS GIS Cut Line= 4
2196312.29458166570624.1499130122196357.59927059570653.329204188
2196448.20864845570831.476455577 2196497.3527178  570849.1376055
#Sta/Elev= 30
       0 2600.94     9.4 2598.49    28.4 2591.34    42.7 2588.34      47 2586.49
    58.2 2579.58    67.2 2576.89    71.7 2576.12    97.3 2575.85   103.42572.853
   109.2 2571.86   118.2 2571.96   130.2 2572.85     139 2572.84   152.4 2574.24
   156.9 2573.66   161.4 2573.77   165.9 2574.67   174.9 2574.97   183.6    2577
   192.5 2578.06   225.2 2576.25   242.2 2576.03   253.8 2574.43     258 2575.74
   262.2 2578.44   273.8  2589.8   287.7 2600.24   292.6 2602.86     306 2604.67
#Mann= 3 ,-1,0
       0      .1       0   103.4    .045       0   130.2      .1       0
#XS Ineff= 2 , 0
                           235.3         2579.06
Permanent Ineff=
       F       F
Bank Sta=103.4,130.2
XS Rating Curve= 0 ,0
Exp/Cntr(USF)=0,0
Exp/Cntr=0.3,0.1

Type RM Length L Ch R = 1 ,2423    ,231.6,227,220.5
XS GIS Cut Line= 2
2196194.74100188570741.2387903472196462.43589941570963.977292876
#Sta/Elev= 30
       0 2617.74     7.1    2613      18 2604.44    32.2 2595.93    53.9 2585.02
    62.4 2579.82    80.5  2570.1    86.2  2567.8    94.7 2566.79   106.1 2566.86
   111.7 2567.79   116.3 2570.01   120.3 2570.86   143.7 2571.29   168.6 2570.63
   179.9 2569.53   194.1 2569.52   204.8 2571.61   225.6 2571.34   242.4 2572.11
   251.6 2571.38   276.5 2572.55   282.2  2573.5   288.1 2575.52   293.3 2579.17
   299.2 2584.34   303.7 2586.71   324.8 2588.93   334.9 2595.23   348.2 2598.66
#Mann= 3 ,-1,0
       0      .1       0    86.2    .045       0   111.7      .1       0
#XS Ineff= 2 , 0
                           143.7            2574
Permanent Ineff=
       F       F
Bank Sta=86.2,111.7
XS Rating Curve= 0 ,0
Exp/Cntr(USF)=0,0
Exp/Cntr=0.3,0.1

Type RM Length L Ch R = 1 ,2196    ,147.2,154,160
XS GIS Cut Line= 4
2196102.44832418570956.5017543552196143.91363269570997.967062868
2196345.86504268571048.6468843832196404.99150111571076.290423392
#Sta/Elev= 30
       0 2578.95     7.4  2575.2    19.4 2567.71    24.3 2566.11    41.3  2565.7
    58.9 2564.43    67.2 2565.19    83.7 2565.08      96 2563.61   108.4 2563.65
   112.5 2562.84   116.6 2561.08  118.982560.712     129 2559.72   137.2 2559.56
   141.4 2559.73   145.5 2560.72   160.4 2563.46   174.4 2563.85     195 2566.09
     228 2566.94   240.4 2568.41   252.8 2568.81   269.4  2570.1   282.7  2572.4
   295.9 2572.95   305.9 2575.27   315.3 2578.77   324.8 2583.07   332.1 2586.92
#Mann= 3 ,-1,0
       0      .1       0  118.98    .045       0   145.5      .1       0
Bank Sta=118.98,145.5
XS Rating Curve= 0 ,0
Exp/Cntr(USF)=0,0
Exp/Cntr=0.3,0.1

Type RM Length L Ch R = 1 ,2042    ,250,251.8,255.1
XS GIS Cut Line= 3
 2196025.1089264571048.7853872292196209.39918646571213.110869114
2196242.41785805  571223.0932582
#Sta/Elev= 30
       0 2587.28     6.6 2580.72    10.9 2577.66    14.8 2576.31    25.5 2575.29
    30.9 2574.04    33.6 2572.56    36.7 2570.58    41.6 2564.96    44.9 2562.18
    47.8 2560.03    50.6 2558.96    59.1 2557.91    84.5 2558.69   105.9 2557.83
   111.3 2556.89  117.342554.615     122 2553.71  139.962554.616   156.9 2558.11
     181 2557.16   202.4 2555.41   209.3 2556.43   220.6 2556.22   231.9 2556.91
   240.4 2560.13   258.2 2571.59   270.7 2580.89   274.9 2583.43   281.4 2586.04
#Mann= 3 ,-1,0
       0      .1       0  117.34    .045       0  139.96      .1       0
#XS Ineff= 2 , 0
                           209.1         2559.55
Permanent Ineff=
       F       F
Bank Sta=117.34,139.96
XS Rating Curve= 0 ,0
Exp/Cntr(USF)=0,0
Exp/Cntr=0.3,0.1

Type RM Length L Ch R = 1 ,1790    ,298.3,300.8,301.7
XS GIS Cut Line= 2
2195923.74928337571268.3979471312196086.53901309571484.171126616
#Sta/Elev= 30
       0 2579.94      11 2576.16    32.3 2566.12    41.1 2560.32    47.2 2554.76
    53.8 2550.22    60.8  2547.2    66.1 2546.48   70.212545.206    76.1 2544.38
      87 2544.44    94.72545.206   100.8 2548.83   103.7 2549.31   111.2 2549.51
   126.2 2547.82   132.2 2547.93   136.3 2548.49   141.3 2550.84   143.7 2551.09
   176.4 2547.79   181.4 2547.61   191.4 2548.66   200.8 2548.87   211.4 2548.59
   221.4 2547.45   226.5 2549.17   236.5 2556.08   246.7 2564.45   270.3 2586.03
#Mann= 3 ,-1,0
       0      .1       0   70.21    .045       0    94.7      .1       0
#XS Ineff= 2 , 0
                          201.81         2553.32
Permanent Ineff=
       F       F
Bank Sta=70.21,94.7
XS Rating Curve= 0 ,0
Exp/Cntr(USF)=0,0
Exp/Cntr=0.3,0.1

Type RM Length L Ch R = 1 ,1490    ,313.9,310.1,304.8
XS GIS Cut Line= 3
2195682.63619313571397.4011291722195780.92433182571600.120415235
2195849.26530326571642.353599832
#Sta/Elev= 30
       0 2584.49     4.2 2582.76     8.6 2579.68    21.9 2566.36    35.3 2563.41
    39.8 2561.15    48.9 2553.34    57.9 2548.78    66.8 2542.06    75.8 2537.22
    79.8 2536.22      86  2536.3     102 2538.99   110.9 2539.12   126.7 2537.99
  135.942533.618   150.7 2532.58  155.372533.615   177.6 2544.94     182 2544.79
   186.9 2543.34   199.8 2543.16   204.6 2543.94   208.7 2545.72   225.3 2546.62
   233.8 2548.81   247.9 2555.04   271.4 2567.69   298.2 2574.79   305.6 2575.42
#Mann= 4 ,-1,0
       0     .08       0      90      .1       0  135.94    .045       0
  155.37      .1       0
#XS Ineff= 2 , 0
           106.4    2542
Permanent Ineff=
       F       F
Bank Sta=135.94,155.37
XS Rating Curve= 0 ,0
Exp/Cntr(USF)=0,0
Exp/Cntr=0.3,0.1

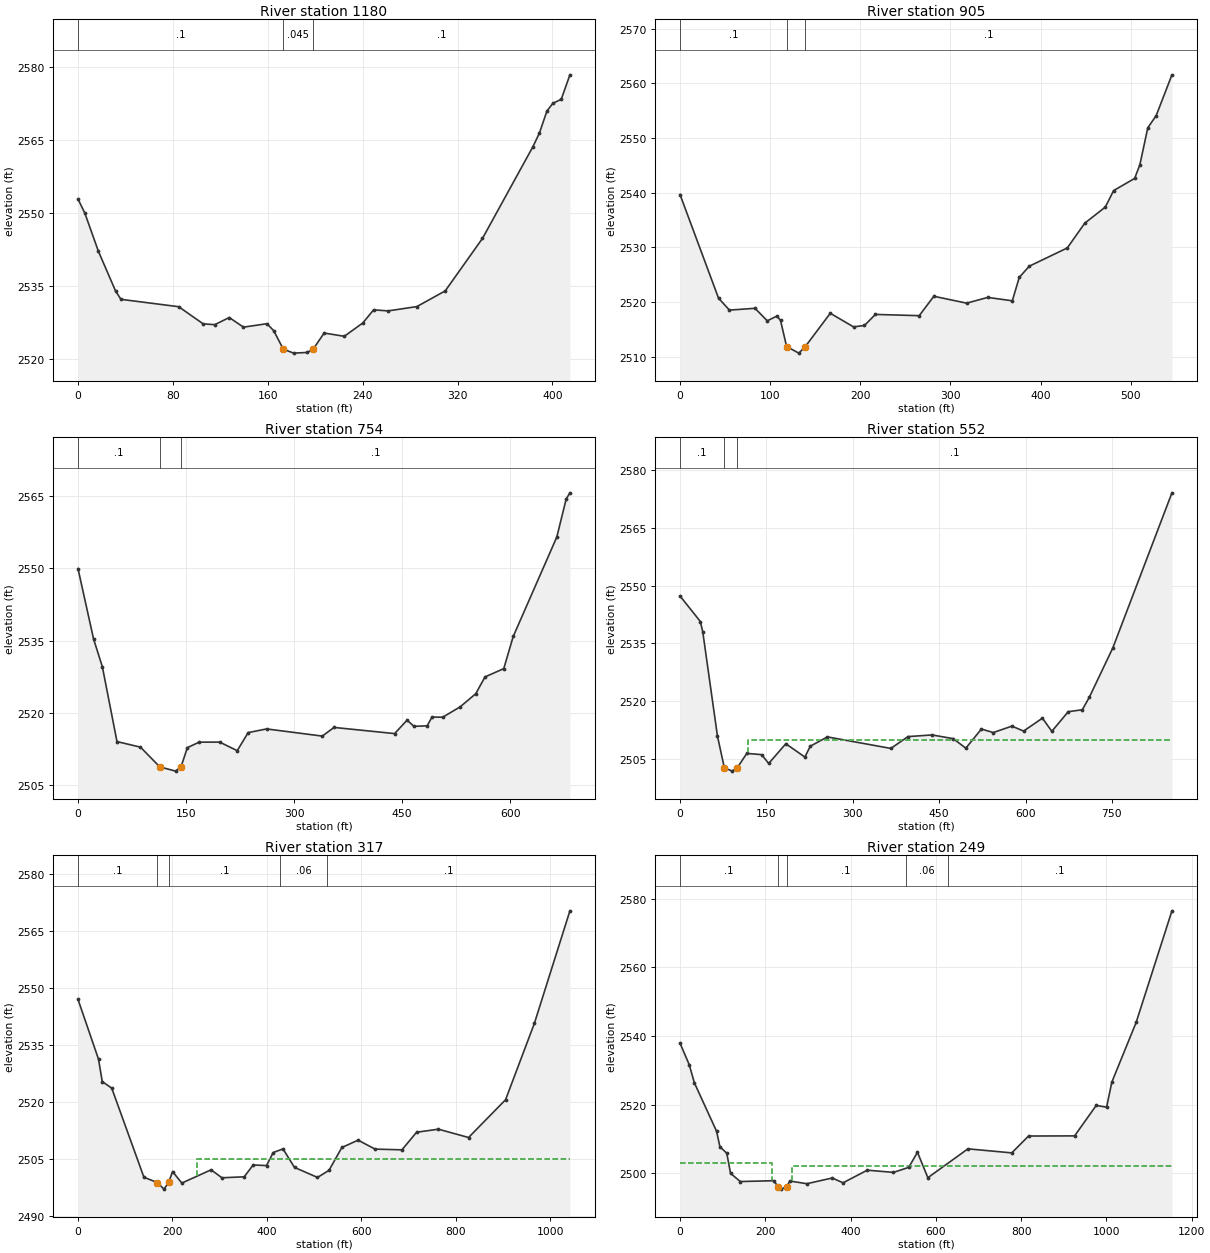
Type RM Length L Ch R = 1 ,1180    ,266.3,274.2,282.8
XS GIS Cut Line= 2
2195363.19974236571589.3701500652195675.72530838571861.966159734
#Sta/Elev= 30
       0 2552.91     5.8 2549.98    17.2 2542.16    31.7 2533.98    36.2 2532.29
    84.9 2530.77   105.5 2527.25   115.3 2527.08   127.5 2528.55   139.5 2526.57
   159.3 2527.28     165 2525.84  173.04 2522.05   181.8 2521.23   193.3 2521.37
  198.252522.048   207.5 2525.36   224.5 2524.69   240.1 2527.43   249.2 2530.13
   261.4 2529.91   285.7  2530.8   309.6 2534.03     341 2544.82   383.5 2563.66
     389 2566.47   395.3 2570.99   400.3 2572.57   407.4 2573.42   414.7 2578.44
#Mann= 3 ,-1,0
       0      .1       0  173.04    .045       0  198.25      .1       0
Bank Sta=173.04,198.25
XS Rating Curve= 0 ,0
Exp/Cntr(USF)=0,0
Exp/Cntr=0.3,0.1

Type RM Length L Ch R = 1 ,905     ,150.8,151.2,150.8
XS GIS Cut Line= 3
2195239.57169291571683.0510322612195290.25151442572003.255359112
2195479.14903098572119.204647732
#Sta/Elev= 30
       0 2539.66    42.7 2520.72    54.8 2518.53    83.2 2518.86    96.8 2516.57
   107.4 2517.43   111.5 2516.65  118.242511.867   131.8 2510.66  139.032511.868
   166.7 2517.95   192.5 2515.46   204.6 2515.72   216.8 2517.74   265.4 2517.51
   281.6 2521.06     318  2519.8   341.5 2520.85   368.7 2520.23   376.4 2524.51
   387.5 2526.56   429.7  2529.9   449.1 2534.43   471.9 2537.38   481.1 2540.39
   504.4 2542.61   510.2  2545.1     519 2551.87   528.3 2554.09   545.8 2561.56
#Mann= 3 ,-1,0
       0      .1       0  118.24    .045       0  139.03      .1       0
Bank Sta=118.24,139.03
XS Rating Curve= 0 ,0
Exp/Cntr(USF)=0,0
Exp/Cntr=0.3,0.1

Type RM Length L Ch R = 1 ,754     ,204.2,202.5,200.9
XS GIS Cut Line= 3
2195089.75711071571719.9901219492195155.63036689572070.379782488
2195456.96547495 572195.11850164
#Sta/Elev= 30
       0 2549.95    21.6 2535.34    33.8 2529.56    54.1 2514.02    86.7 2512.86
  113.542508.762   135.5 2507.88     143  2508.8   151.8 2512.76   168.1  2513.9
   196.6 2513.91     221 2512.13   236.1 2515.88   261.7 2516.65     339 2515.16
   355.3 2516.96   439.4 2515.68   456.7 2518.47   466.2 2517.19   484.6 2517.29
   491.3 2519.12   506.1 2519.08   530.3 2521.23     552 2523.96   564.9 2527.46
   590.9 2529.18     604 2535.86   664.5 2556.52   677.5 2564.41   682.7 2565.71
#Mann= 3 ,-1,0
       0      .1       0  113.54    .045       0     143      .1       0
Bank Sta=113.54,143
XS Rating Curve= 0 ,0
Exp/Cntr(USF)=0,0
Exp/Cntr=0.3,0.1

Type RM Length L Ch R = 1 ,552     ,237.6,234.8,232.4
XS GIS Cut Line= 3
2194884.81294229571795.9288165472195021.49488517572182.938362668
2195456.88062456572268.940484029
#Sta/Elev= 30
       0 2547.33    35.3  2540.7    39.5 2537.99      65 2510.95   76.852502.806
    90.4 2501.88    99.72502.807   115.9 2506.48   141.6 2506.16     154 2503.87
   183.7 2508.99   216.8 2505.53   226.2 2508.35   255.9 2510.76   366.1 2507.77
   395.8 2510.84   437.6 2511.27   474.3 2510.31   496.3 2507.84   523.3  2512.8
     544 2511.89   576.3 2513.56   596.6 2512.27   629.3 2515.63   645.6 2512.21
   674.1  2517.3   698.6 2517.81   710.8 2521.07   751.6 2533.87   854.2  2574.1
#Mann= 3 ,-1,0
       0      .1       0   76.85    .045       0    99.7      .1       0
#XS Ineff= 2 , 0
                        117.3374            2510
Permanent Ineff=
       F       F
Bank Sta=76.85,99.7
XS Rating Curve= 0 ,0
Exp/Cntr(USF)=0,0
Exp/Cntr=0.3,0.1

Type RM Length L Ch R = 1 ,317     ,68.7,68.2,68.5
BEGIN DESCRIPTION:
Structure XS 4
END DESCRIPTION:
XS GIS Cut Line= 4
2194664.43250631571809.7505860512194665.96825848571921.860494253
2194828.75798819572181.4026105012195442.29097897 572292.74464262
#Sta/Elev= 30
       0 2546.99    43.4 2531.24    51.4 2525.32    71.4 2523.62   139.6 2500.11
  168.292498.704   182.1 2496.98  192.052498.748   200.3 2501.61   219.9 2498.58
   281.9 2502.07   304.9 2499.97   352.1 2500.23     371 2503.35   399.3 2503.19
   413.5 2506.63   434.2 2507.59   458.6 2502.71   507.3 2500.06   531.7 2501.94
   558.9 2507.96   593.3 2509.89   629.3 2507.53   686.2 2507.34   717.2 2511.98
   763.5 2512.78   827.3 2510.59   905.7 2520.55   966.7 2540.67    1042 2570.35
#Mann= 5 ,-1,0
       0      .1       0  168.29    .045       0  192.05      .1       0
  428.49     .06       0  528.49      .1       0
#XS Ineff= 2 , 0
                           252.5            2505
Permanent Ineff=
       F       F
Bank Sta=168.29,192.05
XS Rating Curve= 0 ,0
Exp/Cntr(USF)=0,0
Exp/Cntr=0.5,0.3

Type RM Length L Ch R = 1 ,249     ,42,41.7,41.1
BEGIN DESCRIPTION:
Structure XS 3
END DESCRIPTION:
XS GIS Cut Line= 6
2194557.80808574571799.5752426872194557.80808574571918.056577121
2194610.31958389571964.384053282 2194716.7464612572113.117310641
2194797.66054325572198.3660756612195450.75277696572321.182093062
#Sta/Elev= 30
       0 2537.93    21.6 2531.66    33.6  2526.4    85.6  2512.3    93.6 2507.75
   109.6 2505.89   118.5 2500.01   141.3 2497.63   219.2 2497.87   230.42496.145
   236.5 2495.42  250.212496.151   257.5 2497.78   297.4    2497   356.9 2498.66
   382.3 2497.26   439.1 2500.94   500.5  2500.3   536.4 2501.76   556.8 2506.17
   581.2 2498.75   675.2 2507.16     778 2505.98   817.3 2510.89   925.3 2510.93
     976  2519.8  1000.4 2519.29  1012.6 2526.58  1069.6 2543.97  1153.6  2576.5
#Mann= 5 ,-1,0
       0      .1       0   230.4    .045       0  250.21      .1       0
  529.09     .06       0  629.09      .1       0
#XS Ineff= 2 , 0
          216.19 2502.96  262.49         2502.24
Permanent Ineff=
       F       F
Bank Sta=230.4,250.21
XS Rating Curve= 0 ,0
Exp/Cntr(USF)=0,0
Exp/Cntr=0.5,0.3