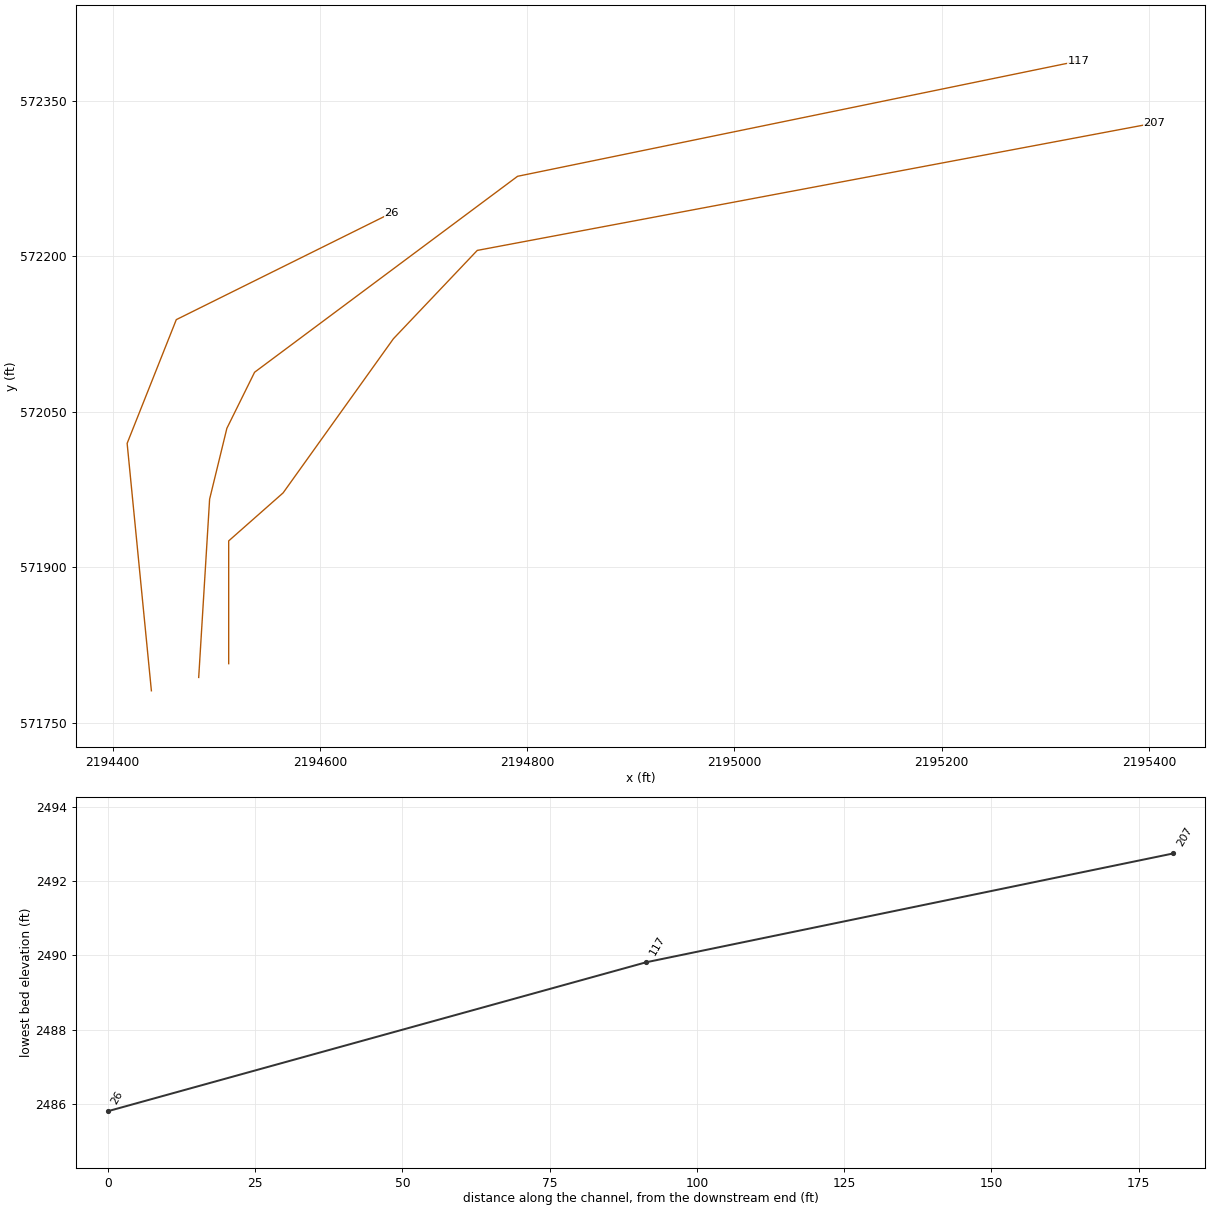
HEC-RAS study BIGRN_1.prj: BIGRN_1

--- BIGRN_1.g01 (geometry) --- (continued)

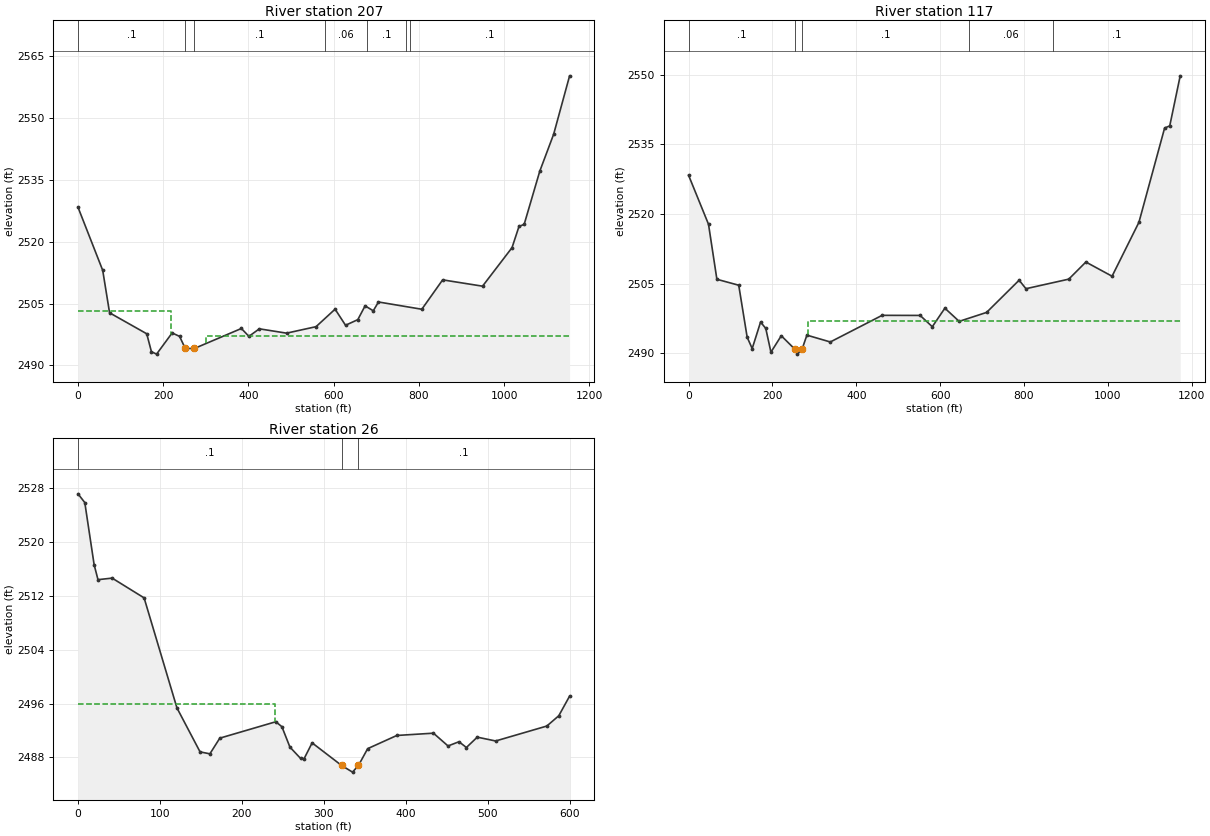
Type RM Length L Ch R = 1 ,207     ,88,89.5,93.2
BEGIN DESCRIPTION:
Structure XS 2
END DESCRIPTION:
XS GIS Cut Line= 6
2194512.04330546571807.0625678962194512.04330546 571925.54390233
2194564.55480361571971.8713784912194670.98168092 572120.60463585
2194751.89576297 572205.853400872195404.98799668572328.669418271
#Sta/Elev= 30
       0 2528.32      58 2513.03    74.1 2502.75   161.3 2497.67   172.3 2493.33
   184.4 2492.74   220.9 2497.87   238.4 2497.04  251.682494.113   273.1 2494.11
   383.4 2498.95   401.1 2497.05   425.6 2498.87   489.4 2497.82   558.6 2499.39
   603.3 2503.63   627.8 2499.73   656.6 2501.09   673.7 2504.43   692.9 2503.24
   705.1 2505.37   806.8 2503.61   855.7 2510.73   949.3  2509.2  1018.5 2518.53
  1034.8 2523.66    1047 2524.18  1083.6 2537.05  1116.2 2546.01  1153.6 2560.15
#Mann= 7 ,-1,0
       0      .1       0  251.68    .045       0   273.1      .1       0
  579.09     .06       0  679.09      .1       0  769.09     .06       0
  779.09      .1       0
#XS Ineff= 2 , 0
          217.75 2503.27  301.13          2497.1
Permanent Ineff=
       F       F
Bank Sta=251.68,273.1
XS Rating Curve= 0 ,0
Exp/Cntr(USF)=0,0
Exp/Cntr=0.5,0.3

Type RM Length L Ch R = 1 ,117     ,88.9,91.4,91.6
BEGIN DESCRIPTION:
Structure XS 1
END DESCRIPTION:
XS GIS Cut Line= 6
2194483.10302891571793.7802719832194493.63630852571965.823838947
2194510.28717648572034.1726108642194537.03230048572088.284838474
2194790.79998857572277.366645293 2195332.5442443 572388.70099865
#Sta/Elev= 30
       0 2528.35    47.5  2517.8    67.5 2505.94   119.6 2504.66   139.7 2493.46
   151.7 2491.01   171.7 2496.72   184.1 2495.35   196.4 2490.23   221.1 2493.77
     254 2490.82   259.5 2489.81  270.582490.851   282.2  2493.9     338 2492.43
   461.6 2498.17   552.3 2498.15   581.3 2495.72   611.3 2499.71   645.4 2496.87
   710.8  2498.8   788.4 2505.74   804.7 2503.91   906.8 2505.97   947.6 2509.66
  1010.1  2506.6  1074.2 2518.23  1135.4 2538.53  1147.7 2539.01  1172.6 2549.79
#Mann= 5 ,-1,0
       0      .1       0     254    .045       0  270.58      .1       0
  669.54     .06       0  869.54      .1       0
#XS Ineff= 2 , 0
         171.446    2496 285.031            2497
Permanent Ineff=
       F       F
Bank Sta=254,270.58
XS Rating Curve= 0 ,0
Exp/Cntr(USF)=0,0
Exp/Cntr=0.3,0.1

Type RM Length L Ch R = 1 ,26      ,,,
XS GIS Cut Line= 4
2194437.45881727571780.9062635712194414.05152924572019.660601399
2194461.48788191572139.0504009812194669.14433202572242.009608294
#Sta/Elev= 30
       0 2527.17     8.3 2525.87    19.7 2516.63    24.4 2514.41    41.7 2514.64
    80.7  2511.7   120.8 2495.34     149 2488.81     161 2488.52   173.1 2490.85
   241.5 2493.29   248.9 2492.55   258.7 2489.52   271.7 2487.84     276  2487.8
   285.8 2490.15   321.82486.788   335.1  2485.8   342.42486.799   353.6 2489.29
   389.2 2491.25   433.9 2491.59   451.7 2489.69   465.1 2490.32   474.1 2489.46
   487.4    2491   509.8 2490.43   572.3 2492.65   586.9 2494.18   600.1  2497.1
#Mann= 3 ,-1,0
       0      .1       0   321.8    .045       0   342.4      .1       0
#XS Ineff= 2 , 0
         240.106    2496
Permanent Ineff=
       F       F
Bank Sta=321.8,342.4
XS Rating Curve= 0 ,0
Exp/Cntr(USF)=0,0
Exp/Cntr=0.3,0.1
LCMann Table=0

Chan Stop Cuts=-1
Use User Specified Reach Order=0
Composite Channel Slope=5